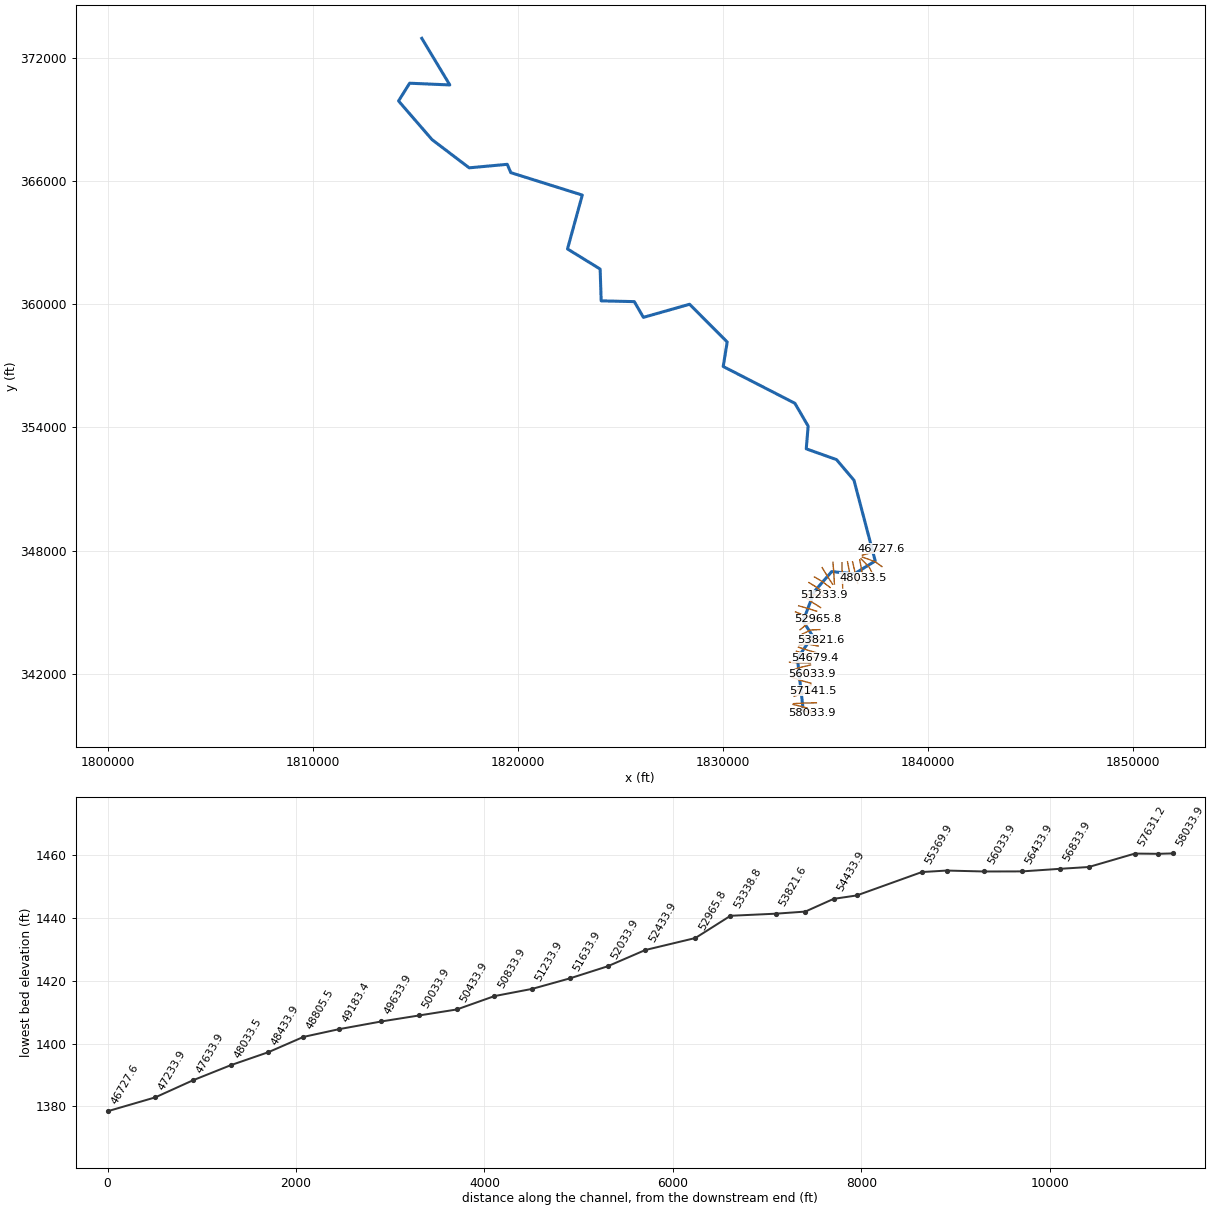
--- WhtdyCrk.prj (project) ---

Proj Title=WhtdyCrk
Current Plan=p01
Default Exp/Contr=0,0
English Units
Geom File=g01
Flow File=f01
Plan File=p01
BEGIN DESCRIPTION:
END DESCRIPTION:
DSS Export Rating Curves= 0
DSS Export Rating Curve Sorted= 0
DSS Export Volume Flow Curves= 0
DXF OffsetX= 0
DXF OffsetY= 0
DXF ScaleX= 0
DXF ScaleY= 0

--- WhtdyCrk.p01 (plan) ---

Plan Title=Floodplain
Program Version=4.00
Geom File=g01
Flow File=f01
K Sum by GR=0
Std Step Tol=0.01
Critical Tol=0.01
Num of Std Step Trials=20
Max Error Tol=0.3
Flow Tol Ratio=0.001
Split Flow NTrial=30
Split Flow Tol=0.02
Split Flow Ratio=0.02
Log Output Level=0
Friction Slope Method=1
Unsteady Friction Slope Method=2
Unsteady Bridges Friction Slope Method=1
Global Log Level=0
CheckData=False
Run HTab=0
Run UNet=0
Run PostProcess=0
UNET Theta=0
UNET Theta Warmup=0
UNET ZTol=0
UNET ZSATol=0
UNET MxIter=0
UNET MaxInSteps=0
UNET DtIC=0
UNET DtMin=0
UNET MaxCRTS=0
UNET WFStab=0
UNET SFStab=0
UNET WFX=0
UNET SFX=0
UNET DSS MLevel=0
UNET DZMax Abort=0
UNET Convert EG Bridges=0
UNET Use Existing IB Tables=0
UNET Froude Limit=0
UNET Froude Power=0
Write IC File=0
Echo Input=False
Echo Output=False
Write Detailed=0

--- WhtdyCrk.f01 (steady flow) ---

Flow Title=NFF Regression Equation
Program Version=4.00
Number of Profiles=1
Profile Names=P100yr
River Rch & RM=WhtdyCrk,Main      ,58033.9
1356.159
River Rch & RM=WhtdyCrk,Main      ,57631.2
2234.733
River Rch & RM=WhtdyCrk,Main      ,52433.9
2397.153
River Rch & RM=WhtdyCrk,Main      ,43233.9
2639.999
River Rch & RM=WhtdyCrk,Main      ,42761.3
2957.697
River Rch & RM=WhtdyCrk,Main      ,41594.8
3104.094
River Rch & RM=WhtdyCrk,Main      ,33315.8
3441.475
River Rch & RM=WhtdyCrk,Main      ,32833.9
3878.502
River Rch & RM=WhtdyCrk,Main      ,29233.9
4118.129
River Rch & RM=WhtdyCrk,Main      ,23626.6
4520.971
River Rch & RM=WhtdyCrk,Main      ,16875.5
4807.349
River Rch & RM=WhtdyCrk,Main      ,89
5236.833
River Rch & RM=WhtdyCrk,Main      ,89
5237.940
Boundary for River Rch & Prof#=WhtdyCrk,Main      ,1
Up Type=0
Dn Type=3
Dn Slope=0.004246

--- WhtdyCrk.g01 (geometry) ---

Geom Title=USGS 3m DEM
Program Version=4.00

River Reach=WhtdyCrk        ,Main
Reach XY= 30
     1833899.572      340217.437       1833615.2      342747.989
     1834363.926      343827.883     1833892.372      344558.611
     1834439.519       346002.07     1835289.035      346973.975
     1836397.727      346865.985     1837412.827      347492.324
       1836377.6      351424.376     1835523.548      352434.025
     1834047.109      352959.596     1834140.467       354066.06
     1833493.877       355179.44     1829995.918      356973.563
     1830191.773      358166.894     1828355.587      360007.467
     1826103.164      359367.877     1825658.046      360135.422
      1824042.37      360172.709     1823992.917      361723.009
     1822400.142      362703.549     1823121.183      365329.351
      1819633.77      366423.101     1819460.158      366828.917
      1817604.69      366657.476     1815792.624      368031.174
     1814158.509      369917.025     1814698.874       370782.91
     1816658.509      370698.275     1815291.322       372970.41

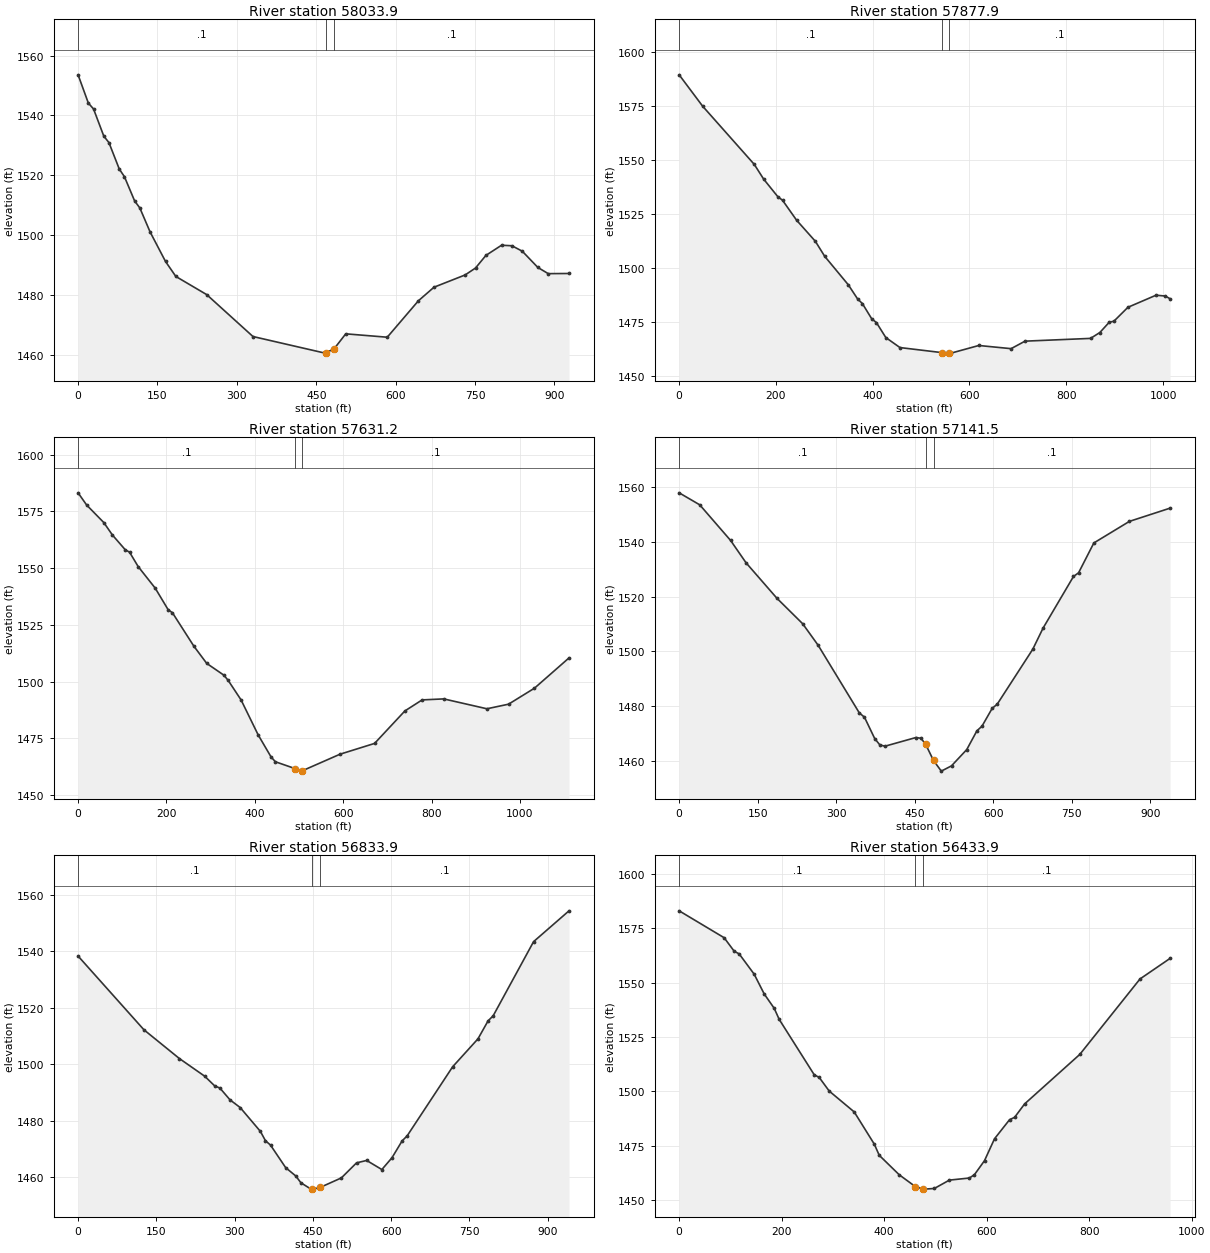
Type RM Length L Ch R = 1 ,58033.9 ,167.574,156.025,150.22
XS GIS Cut Line= 3
      1833429.25      340273.353     1833903.196      340226.757
     1834323.766      340063.202
#Sta/Elev= 30
       0 1553.55    19.4 1544.11    29.2 1542.16    48.6 1533.08    58.3 1530.93
    77.8 1522.11    87.5 1519.57   106.9 1511.43   116.6 1509.14   136.1 1501.09
   165.2 1491.25   184.7 1486.25     243 1480.19   330.4  1466.2   466.5 1460.66
   468.7 1460.82   483.7  1462.1   505.7  1467.1   584.1 1465.97     643 1478.14
   672.4 1482.66   731.3 1486.76   750.9 1489.07   770.5 1493.28     800 1496.67
   819.6  1496.5   839.2 1494.68   868.6 1489.26   888.2 1487.19   927.5 1487.24
#Mann= 3 , 0 , 0
       0      .1       0   468.7    .045       0   483.7      .1       0
Bank Sta=468.7,483.7
XS Rating Curve= 0 ,0
Exp/Cntr=0.3,0.1

Type RM Length L Ch R = 1 ,57877.9 ,227.994,246.716,262.247
XS GIS Cut Line= 4
     1833399.024      340499.791     1833889.699      340381.213
     1834082.029      340325.307     1834314.548      340121.075
#Sta/Elev= 30
       0 1589.53    48.5    1575   155.3    1548   174.7 1541.17   203.9 1533.04
   213.6  1531.4   242.7 1522.14   281.5 1512.36   300.9 1505.37   349.5 1492.22
   368.9 1485.61   378.6 1483.53     398 1476.42   407.7 1474.69   427.1 1467.75
   456.3 1463.11     543 1460.77     558 1460.54     562 1460.53   619.3 1464.07
     686  1462.6   714.8 1466.08   850.2 1467.36   869.5 1470.09   888.8 1474.84
   898.5 1475.33   927.5 1481.78   985.6 1487.38  1004.9 1486.99  1014.6 1485.72
#Mann= 3 , 0 , 0
       0      .1       0     543    .045       0     558      .1       0
Bank Sta=543,558
XS Rating Curve= 0 ,0
Exp/Cntr=0.3,0.1

Type RM Length L Ch R = 1 ,57631.2 ,484.554,489.736,497.41
XS GIS Cut Line= 3
     1833432.408      340536.989     1833936.262      340567.871
     1834542.629      340577.238
#Sta/Elev= 30
       0 1583.22    19.4 1577.84    58.2 1570.12    77.7 1564.64   106.8 1558.13
   116.5 1557.07   135.9 1550.76   174.7 1541.19   203.9 1531.71   213.6 1530.38
   262.1 1515.65   291.2 1508.07   330.1 1502.87   339.8 1500.56   368.9 1491.99
   407.7 1476.54   436.8 1466.86   446.6 1464.74   490.9 1461.74   504.8 1460.61
   505.9 1460.63   592.8 1468.06   671.1 1472.82   739.6 1487.11   778.7 1491.99
   827.6 1492.43   925.4 1488.08   974.3  1490.1    1033 1497.15  1111.2 1510.49
#Mann= 3 , 0 , 0
       0      .1       0   490.9    .045       0   505.9      .1       0
Bank Sta=490.9,505.9
XS Rating Curve= 0 ,0
Exp/Cntr=0.3,0.1

Type RM Length L Ch R = 1 ,57141.5 ,305.648,307.524,302.47
XS GIS Cut Line= 3
      1833454.69      340897.963     1833888.006      341027.229
     1834354.797      341160.859
#Sta/Elev= 30
       0 1557.88    39.3  1553.5    98.3 1540.49   127.8 1532.34   186.8 1519.39
   235.9 1510.11   265.4 1502.27   344.1 1477.57   353.9 1476.01   373.5 1468.21
   383.4 1465.87   393.2 1465.42   452.2 1468.58   461.9 1468.31   470.8 1466.11
   485.8 1460.21   500.7 1456.32   520.2 1458.25   549.3 1464.18   568.7 1471.03
   578.4 1472.72   597.8  1479.2   607.6 1480.78   675.5 1500.83     695 1508.48
   753.2 1527.36   762.9 1528.69   792.1 1539.59     860 1547.46   937.7 1552.29
#Mann= 3 , 0 , 0
       0      .1       0   470.8    .045       0   485.8      .1       0
#XS Ineff= 2 , 0
           453.5 1468.26
Permanent Ineff=
       F       F
Bank Sta=470.8,485.8
XS Rating Curve= 0 ,0
Exp/Cntr=0.3,0.1

Type RM Length L Ch R = 1 ,56833.9 ,418.674,400,389.817
XS GIS Cut Line= 3
     1833408.754      341085.215     1833808.758      341304.465
     1834276.992      341429.914
#Sta/Elev= 30
       0 1538.32   126.2  1512.2   194.1 1502.02   242.6 1495.76     262 1492.29
   271.7 1491.57   291.2 1487.37   310.6 1484.66   349.4  1476.2   359.1  1472.9
   368.8 1471.34   397.9 1463.34   417.3 1460.39     427    1458   446.4 1455.74
   448.7 1455.76   463.7 1456.32   504.6 1459.72   533.7 1465.05   553.1  1465.9
   582.2 1462.68   601.6 1466.86     621 1472.82   630.7 1474.62   717.9  1499.1
   766.4 1508.99   785.8 1515.37   795.5 1517.14     873 1543.43   940.9 1554.35
#Mann= 3 , 0 , 0
       0      .1       0   448.7    .045       0   463.7      .1       0
#XS Ineff= 2 , 0
                          551.82         1465.58
Permanent Ineff=
       F       F
Bank Sta=448.7,463.7
XS Rating Curve= 0 ,0
Exp/Cntr=0.3,0.1

Type RM Length L Ch R = 1 ,56433.9 ,387.002,400,402.954
XS GIS Cut Line= 3
     1833356.746      341811.523     1833801.022       341662.76
     1834273.547      341535.479
#Sta/Elev= 30
       0 1583.14    87.8 1570.74   107.4 1564.52   117.1  1563.3   146.4 1553.94
   165.9 1544.86   185.5 1538.21   195.2 1533.12   263.5 1507.62   273.3 1506.37
   292.8  1500.1   341.6 1490.48   380.7 1475.67   390.4  1470.5   429.5 1461.51
     461 1456.06     476 1454.99   478.3 1454.92   497.9 1455.22   527.2 1459.07
   566.4 1460.04   576.2  1461.6   595.8 1468.04   615.3 1478.11   644.7 1486.92
   654.5 1487.99   674.1 1494.19   781.7 1516.98   899.2 1551.75   957.9 1561.23
#Mann= 3 , 0 , 0
       0      .1       0     461    .045       0     476      .1       0
Bank Sta=461,476
XS Rating Curve= 0 ,0
Exp/Cntr=0.3,0.1

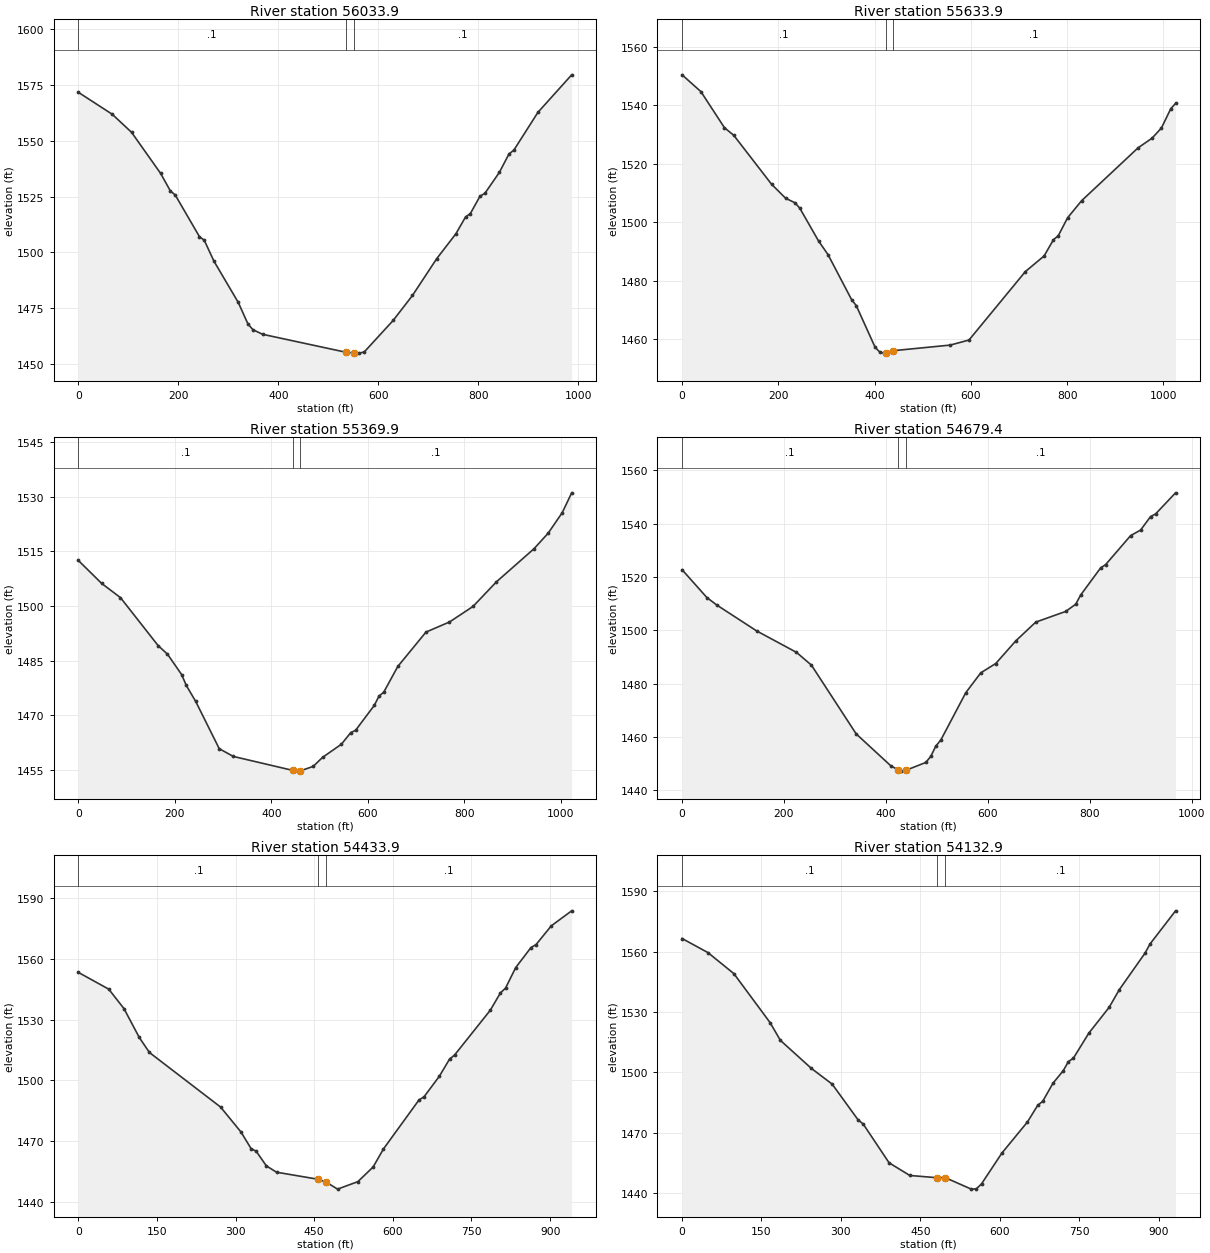
Type RM Length L Ch R = 1 ,56033.9 ,394.567,400,409.855
XS GIS Cut Line= 3
     1833369.038      341919.818     1833900.479      342030.561
     1834339.862      341969.733
#Sta/Elev= 30
       0 1571.71    67.9 1561.86   106.6 1553.77   164.8 1535.35   184.2 1527.52
   193.9 1525.71   242.3 1507.06     252 1505.41   271.4 1496.04   319.9  1477.6
   339.3 1467.95     349 1465.43   368.4 1463.33   535.4 1455.27   550.4 1454.93
   562.1 1454.89   571.8 1455.42   629.6 1469.54   668.2 1480.73   716.4 1497.12
     755 1508.35   774.3 1515.88   783.9  1517.4   803.2 1525.17   812.9 1526.44
   841.8 1535.81   861.1 1544.08   870.7 1545.74   918.9 1562.69   986.4  1579.5
#Mann= 3 , 0 , 0
       0      .1       0   535.4    .045       0   550.4      .1       0
Bank Sta=535.4,550.4
XS Rating Curve= 0 ,0
Exp/Cntr=0.3,0.1

Type RM Length L Ch R = 1 ,55633.9 ,274.274,264.05,257.775
XS GIS Cut Line= 3
     1833279.598      342124.147     1833679.141      342283.964
     1834257.658       342422.38
#Sta/Elev= 30
       0 1550.34    39.1  1544.6      88 1532.27   107.6 1529.62   185.8 1512.95
   215.2 1508.13   234.7 1506.58   244.5 1504.76   283.6 1493.52   303.2 1488.87
   352.1  1473.5   361.9 1471.43     401  1457.2   410.8 1455.54   420.5 1455.19
   422.8 1455.32   437.8 1456.01   557.1 1457.94   596.1 1459.67   713.1 1483.06
   752.1 1488.41   771.6 1493.98   781.4 1495.28   800.9 1501.46   830.1 1507.31
   947.2 1525.36   976.4 1528.68   995.9 1532.17  1015.4  1538.8  1025.2 1540.55
#Mann= 3 , 0 , 0
       0      .1       0   422.8    .045       0   437.8      .1       0
Bank Sta=422.8,437.8
XS Rating Curve= 0 ,0
Exp/Cntr=0.3,0.1

Type RM Length L Ch R = 1 ,55369.9 ,695.139,690.461,681.858
XS GIS Cut Line= 3
     1833229.829      342554.952     1833677.261      342532.703
     1834251.668      342523.413
#Sta/Elev= 30
       0 1512.55    48.7  1506.2    87.6 1502.31   165.6 1489.15     185  1486.8
   214.3  1481.2     224 1478.21   243.5 1473.82   292.2 1460.87   321.4 1458.74
   444.3 1454.92   457.7 1454.71   459.3 1454.74   486.9 1456.01   506.4 1458.49
   545.4  1462.1   564.8 1465.29   574.6 1465.89   613.5 1472.75   623.3 1475.31
     633 1476.35   662.2 1483.43   720.6 1492.86   769.3 1495.63     818 1499.89
   866.7 1506.66   944.6 1515.75   973.8    1520    1003 1525.64  1022.5 1531.07
#Mann= 3 , 0 , 0
       0      .1       0   444.3    .045       0   459.3      .1       0
Bank Sta=444.3,459.3
XS Rating Curve= 0 ,0
Exp/Cntr=0.3,0.1

Type RM Length L Ch R = 1 ,54679.4 ,244,245.488,247.344
XS GIS Cut Line= 3
     1833566.574      343092.845     1834019.383      342938.555
     1834482.255      342777.556
#Sta/Elev= 30
       0 1522.76    48.8  1512.3    68.3  1509.5   146.4 1499.81   224.5 1491.78
   253.8    1487   341.7  1461.2     410 1449.18   424.4 1447.71   429.6 1447.25
   439.4 1447.57   478.4 1450.51   488.2 1452.83     498 1456.66   507.8 1458.93
   556.8 1476.67   586.2 1484.11   615.6  1487.6   654.8 1496.07     694 1503.11
   752.8 1507.12   772.4 1509.81   782.2 1513.27   821.4 1523.45   831.2 1524.68
   880.2 1535.54   899.8 1537.63   919.4 1542.69   929.2 1543.67   968.4 1551.59
#Mann= 3 , 0 , 0
       0      .1       0   424.4    .045       0   439.4      .1       0
Bank Sta=424.4,439.4
XS Rating Curve= 0 ,0
Exp/Cntr=0.3,0.1

Type RM Length L Ch R = 1 ,54433.9 ,298.342,301.086,303.206
XS GIS Cut Line= 3
     1833667.198      343290.739     1834110.001       343147.24
     1834566.108      343012.346
#Sta/Elev= 30
       0 1553.37    58.2 1545.05    87.3 1535.42   116.4 1521.17   135.8 1513.73
   271.5 1486.75   310.3 1474.45   329.7 1466.19   339.4 1464.91   358.8 1457.66
   378.2 1454.53     458 1451.02     473 1449.61   494.6 1446.16   533.4 1449.87
   562.5 1457.13     582 1465.98   649.9 1490.26   659.6 1491.85   688.7 1501.96
   708.1 1510.41   717.9 1512.51   785.8  1534.6   805.2 1543.18   814.9 1545.54
   834.3 1555.69   863.5 1565.64   873.2 1567.11   902.3 1576.38   941.1 1583.78
#Mann= 3 , 0 , 0
       0      .1       0     458    .045       0     473      .1       0
Bank Sta=458,473
XS Rating Curve= 0 ,0
Exp/Cntr=0.3,0.1

Type RM Length L Ch R = 1 ,54132.9 ,307.016,311.234,315.452
XS GIS Cut Line= 3
     1833708.983      343412.855      1834167.87      343435.954
      1834631.82      343345.522
#Sta/Elev= 30
       0 1566.48    48.9 1559.48    97.8 1549.06   166.2 1524.75   185.7 1515.93
   244.4 1501.98   283.5 1494.22   332.4  1476.5   342.2 1474.39     391 1455.16
   430.1 1448.88   481.9 1447.76   496.9 1447.82   546.3  1442.1   555.9 1442.23
   565.6 1444.72   604.2 1460.03   652.4 1475.45   671.7 1483.67   681.3 1485.74
   700.6 1494.67   719.9 1500.84   729.6 1505.36   739.2 1507.11   768.2 1519.48
   806.7 1532.33     826 1541.15   874.3 1559.17   883.9 1563.78   932.1 1580.22
#Mann= 3 , 0 , 0
       0      .1       0   481.9    .045       0   496.9      .1       0
Bank Sta=481.9,496.9
XS Rating Curve= 0 ,0
Exp/Cntr=0.3,0.1

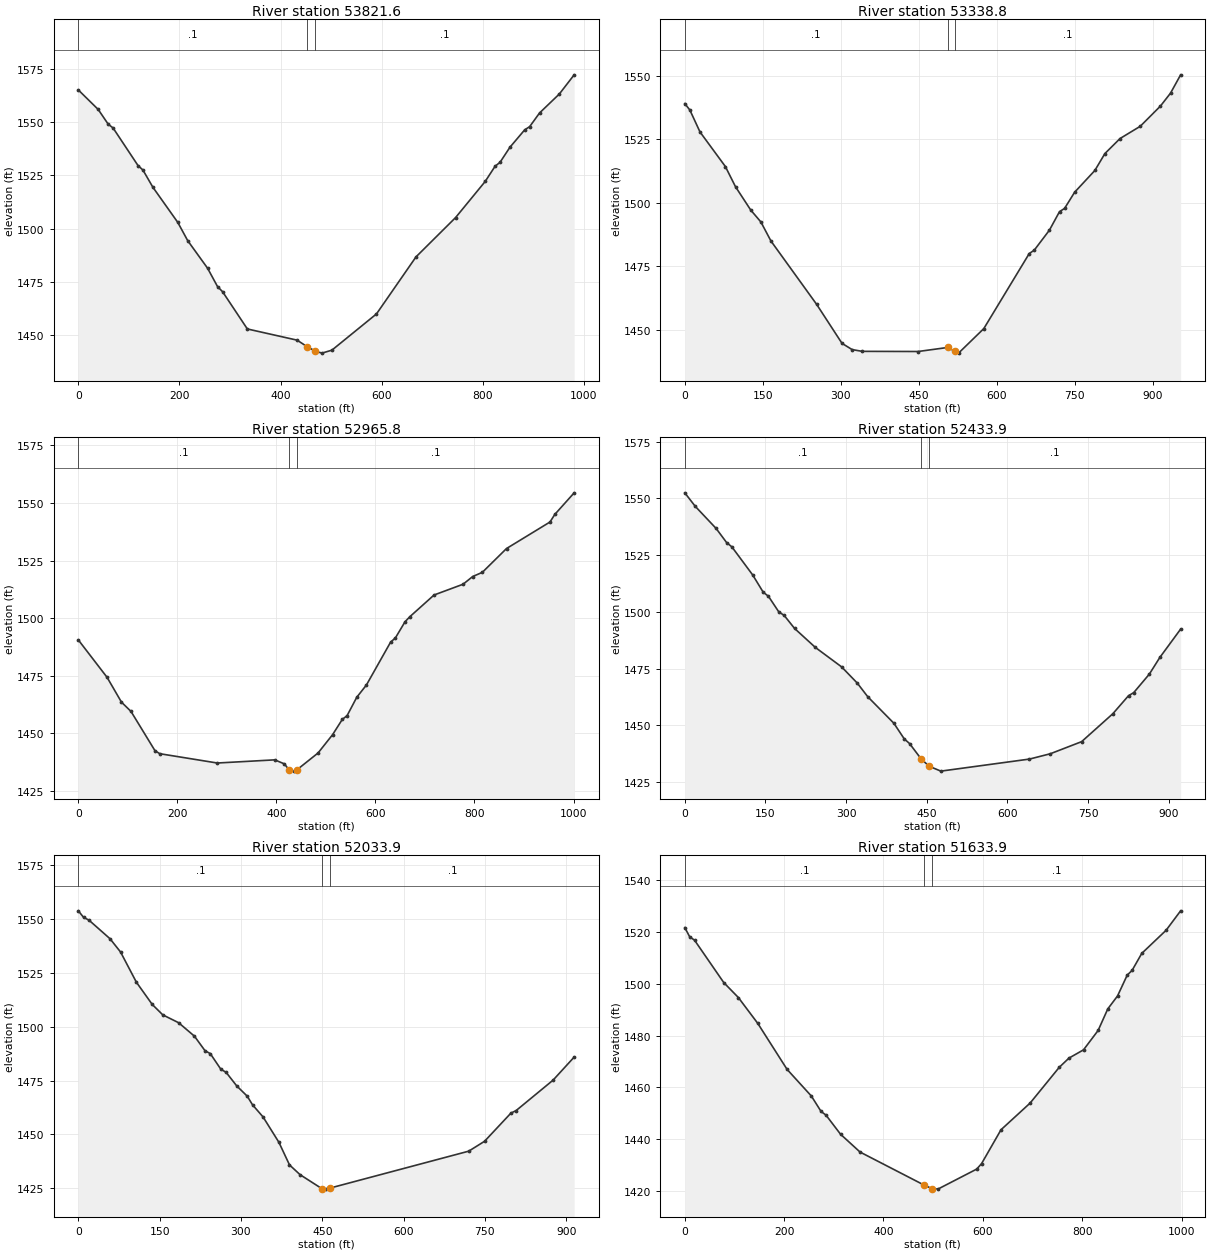
Type RM Length L Ch R = 1 ,53821.6 ,474.47,482.79,484.008
XS GIS Cut Line= 3
     1833801.596      343746.551     1834340.871      343705.707
     1834777.714      343654.315
#Sta/Elev= 30
       0 1565.16    39.3 1555.99      59 1549.09    68.8 1547.26     118 1529.63
   127.8  1527.5   147.5  1519.4   196.7  1502.9   216.3 1494.32   255.7 1481.33
   275.3 1472.72   285.2 1470.34   334.3 1452.79   432.7 1447.53   452.9 1444.41
   467.9 1442.49   481.8 1441.43   501.5 1442.82   589.7 1459.86   667.9 1486.68
   746.1 1505.14   804.7 1522.13   824.3 1529.29   834.1 1531.14   853.6  1538.2
   882.9 1546.42   892.7 1547.91   912.3 1554.35   951.4 1563.26   980.7 1572.27
#Mann= 3 , 0 , 0
       0      .1       0   452.9    .045       0   467.9      .1       0
Bank Sta=452.9,467.9
XS Rating Curve= 0 ,0
Exp/Cntr=0.3,0.1

Type RM Length L Ch R = 1 ,53338.8 ,365.776,373.053,380.165
XS GIS Cut Line= 3
     1833805.215      343903.473     1834259.291      344128.654
     1834705.213      344146.403
#Sta/Elev= 30
       0 1539.14     9.7 1536.63    29.2 1527.97      78 1514.33    97.5 1506.36
   126.7 1497.19   146.2 1492.49   165.7 1484.94   253.4    1460   302.2 1444.61
   321.7 1442.15   341.1 1441.46   448.4  1441.4   505.3 1442.99   520.3 1441.41
   526.2 1440.76   574.8 1450.44   662.1 1480.02   671.8 1481.37   700.9 1489.25
   720.3 1496.55     730 1497.81   749.4 1504.21   788.2 1512.77   807.6 1519.46
   836.7 1525.38   875.5  1530.2   914.3 1538.17   933.7 1543.27   953.1 1550.49
#Mann= 3 , 0 , 0
       0      .1       0   505.3    .045       0   520.3      .1       0
Bank Sta=505.3,520.3
XS Rating Curve= 0 ,0
Exp/Cntr=0.3,0.1

Type RM Length L Ch R = 1 ,52965.8 ,556.446,531.837,516.614
XS GIS Cut Line= 3
     1833741.231      344137.711     1834079.975      344411.313
     1834595.362      344644.917
#Sta/Elev= 30
       0 1490.59    58.1 1474.34    87.1  1463.6   106.4 1459.55   154.8 1442.52
   164.5 1441.22   280.6 1437.18   396.7 1438.55   416.1  1436.8   425.7 1434.17
   435.4 1433.66   440.7  1434.1   484.2 1441.55   513.5 1449.49     533 1456.08
   542.8 1457.76   562.3 1465.71   581.8 1471.04   630.6 1489.63   640.3 1491.46
   659.8 1498.49   669.6 1500.69   718.4 1510.09   776.9 1514.75   796.4  1518.1
   815.9 1519.92   864.7 1530.25   952.5 1541.76   962.3 1545.07  1001.3 1554.42
#Mann= 3 , 0 , 0
       0      .1       0   425.7    .045       0   440.7      .1       0
Bank Sta=425.7,440.7
XS Rating Curve= 0 ,0
Exp/Cntr=0.3,0.1

Type RM Length L Ch R = 1 ,52433.9 ,397.008,400,400.359
XS GIS Cut Line= 3
      1833522.97      345011.414     1833935.518      344839.308
     1834388.339      344696.125
#Sta/Elev= 30
       0 1552.42    19.4 1546.48    58.3 1536.71    77.7 1530.52    87.5 1528.62
   126.3 1516.22   145.8 1508.64   155.5 1506.86   174.9 1499.93   184.6 1498.47
   204.1 1492.68   242.9 1484.29   291.5 1475.76   320.7 1468.61   340.1 1462.62
   388.7 1450.93   408.1 1444.01   417.9 1441.98   439.5 1435.19   454.5 1431.96
   476.1 1429.83   640.9 1435.14   679.6 1437.48   737.8 1442.81   795.9 1455.12
     825 1463.05   834.7 1464.41   863.8 1472.58   883.2 1479.89   921.9 1492.38
#Mann= 3 , 0 , 0
       0      .1       0   439.5    .045       0   454.5      .1       0
Bank Sta=439.5,454.5
XS Rating Curve= 0 ,0
Exp/Cntr=0.3,0.1

Type RM Length L Ch R = 1 ,52033.9 ,407.521,400,394.628
XS GIS Cut Line= 3
     1833678.188      345307.689     1834117.794      345180.616
     1834553.805      345043.831
#Sta/Elev= 30
       0 1553.74     9.7  1550.7    19.5 1549.44    58.4  1540.8    77.9 1534.63
   107.1 1520.62   136.3 1510.32   155.8 1505.47     185 1501.83   214.2 1495.58
   233.7 1488.84   243.4  1487.5   262.9 1480.25   272.6 1478.82   292.1 1472.54
   311.6 1467.74   321.3 1463.75   340.8  1458.1     370 1446.34   389.5 1435.87
   408.9 1431.36   450.1 1424.71   457.6 1424.63   465.1 1425.17   720.1 1442.24
   749.3 1446.82   797.9 1459.88   807.6 1461.09   875.7 1475.19   914.6 1485.88
#Mann= 3 , 0 , 0
       0      .1       0   450.1    .045       0   465.1      .1       0
Bank Sta=450.1,465.1
XS Rating Curve= 0 ,0
Exp/Cntr=0.3,0.1

Type RM Length L Ch R = 1 ,51633.9 ,386.715,400,411.68
XS GIS Cut Line= 3
     1833925.069      345779.806     1834321.935      345492.475
     1834750.586      345219.371
#Sta/Elev= 30
       0 1521.66     9.8 1518.11    19.6  1516.8    78.4 1500.46   107.8 1494.69
     147 1484.69   205.8    1467   254.8 1456.69   274.4 1450.73   284.2 1449.35
   313.6 1441.95   352.8 1435.09   482.5 1422.28   497.5 1421.01   509.5 1420.79
   587.7 1428.52   597.5 1430.64   636.6 1443.69   695.2 1453.98   753.9 1467.78
   773.4 1471.32   802.7 1474.51   832.1 1481.98   851.6 1490.31   871.2 1495.29
   890.7 1503.34   900.5 1505.15     920 1511.71   968.9 1520.61   998.2 1528.12
#Mann= 3 , 0 , 0
       0      .1       0   482.5    .045       0   497.5      .1       0
Bank Sta=482.5,497.5
XS Rating Curve= 0 ,0
Exp/Cntr=0.3,0.1

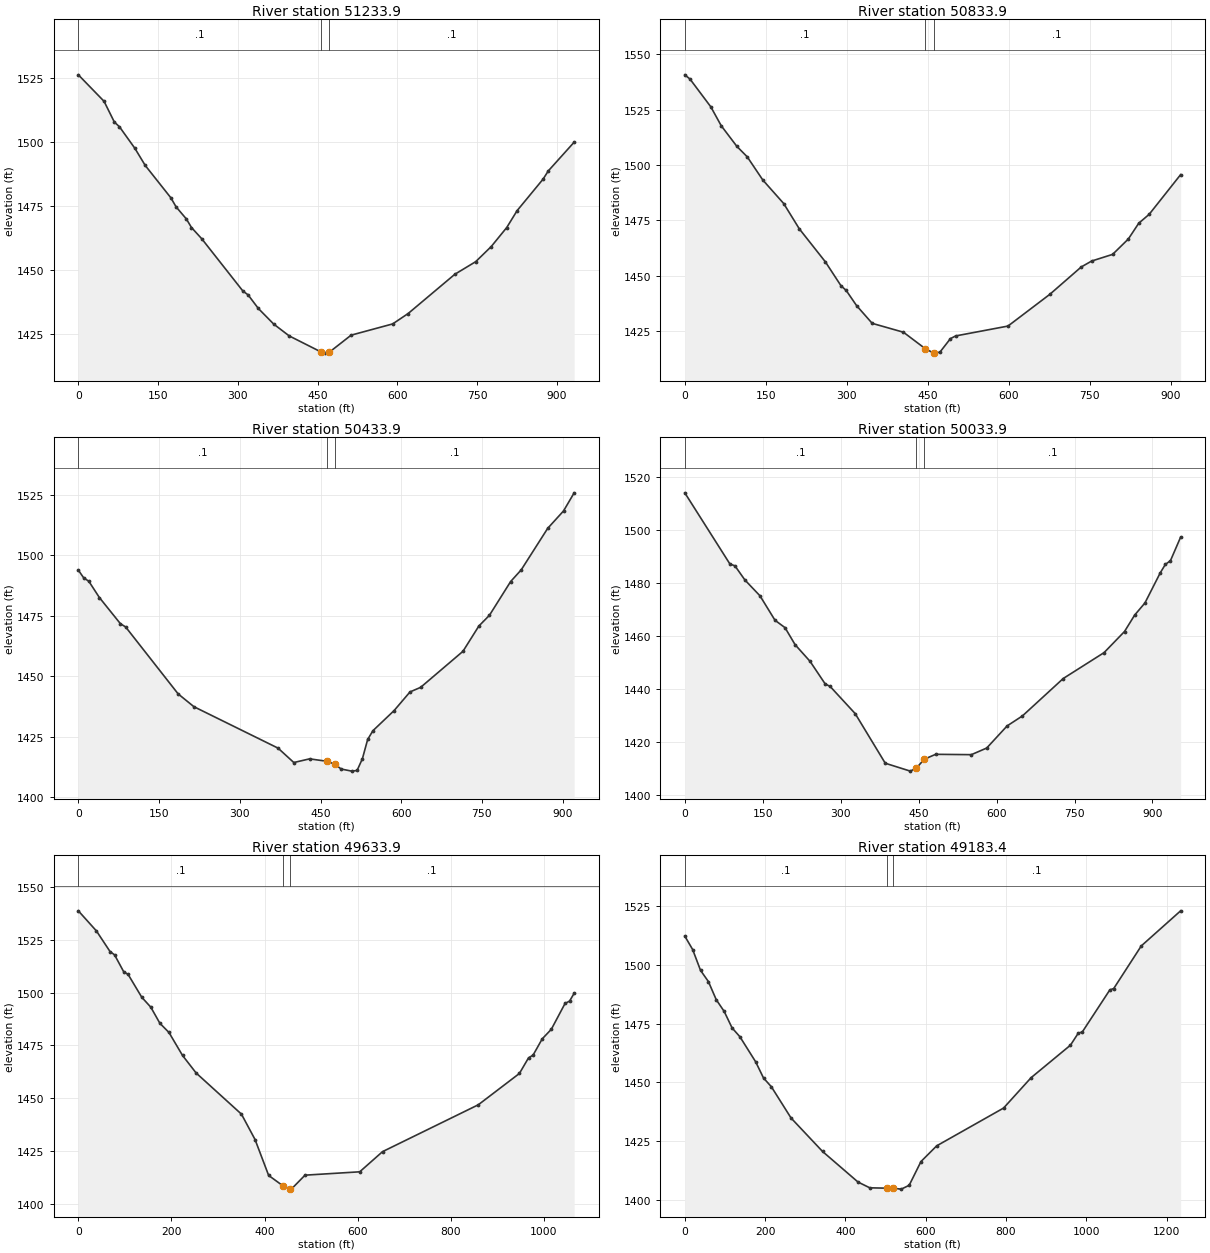
Type RM Length L Ch R = 1 ,51233.9 ,410.354,400,386.856
XS GIS Cut Line= 3
     1833960.181      345882.296     1834422.984      345844.426
     1834890.147      345812.003
#Sta/Elev= 30
       0  1526.3    48.4 1515.94    67.7 1507.84    77.4 1505.97   106.4 1497.54
   125.8 1490.86   174.1 1478.18   183.8 1474.67   203.2 1469.92   212.8 1466.58
   232.2 1462.16   309.6 1441.71   319.2 1440.25   338.6  1434.9   367.6 1428.78
   396.6 1424.18   456.9 1417.86   464.3 1417.44   471.9 1417.77   513.1 1424.47
   591.2 1428.86   620.4 1432.94   708.2 1448.29   747.3  1453.2   776.5  1459.1
   805.8 1466.57   825.3 1473.18   874.1 1485.49   883.9  1488.7   932.6 1499.96
#Mann= 3 , 0 , 0
       0      .1       0   456.9    .045       0   471.9      .1       0
Bank Sta=456.9,471.9
XS Rating Curve= 0 ,0
Exp/Cntr=0.3,0.1

Type RM Length L Ch R = 1 ,50833.9 ,399.492,400,399.831
XS GIS Cut Line= 3
     1834178.815      346439.022     1834565.525        346202.7
     1834933.742      345918.428
#Sta/Elev= 30
       0 1540.73     9.6 1538.83    48.2 1526.28    67.5 1517.75    96.4 1508.46
   115.7 1503.71   144.6 1493.23   183.2 1482.65   212.1 1471.23   260.4 1456.33
   289.3 1445.55   298.9 1443.44   318.2 1436.58   347.1 1428.58     405 1424.57
   445.7 1417.09   460.7 1415.23   462.9 1415.14   472.6 1415.59     492 1421.68
   501.7  1422.9   598.6 1427.35   676.1 1441.67   734.3 1454.02   753.6  1456.7
   792.4  1459.7   821.5 1466.63   840.9 1473.78   860.2 1477.79   918.4 1495.69
#Mann= 3 , 0 , 0
       0      .1       0   445.7    .045       0   460.7      .1       0
Bank Sta=445.7,460.7
XS Rating Curve= 0 ,0
Exp/Cntr=0.3,0.1

Type RM Length L Ch R = 1 ,50433.9 ,412.036,400,391.439
XS GIS Cut Line= 3
      1834446.55      346713.204     1834852.352      346478.593
     1835209.124      346200.136
#Sta/Elev= 30
       0  1493.9     9.8 1490.76    19.5 1489.29    39.1 1482.58    78.1 1471.79
    87.9 1470.42   185.5 1442.76   214.8 1437.48   371.1 1420.37   400.4 1414.42
   429.7 1415.94   461.2 1414.96   476.2 1413.79   488.4 1411.73   508.1 1410.87
   517.9 1411.13   527.8 1415.97   537.6 1423.94   547.4 1427.57   586.8  1435.9
   616.3 1443.59     636 1445.47   714.7 1460.37   744.2  1470.8   763.9 1475.25
   803.3 1489.19   822.9    1494   872.1 1511.15   901.6 1518.36   921.3 1525.83
#Mann= 3 , 0 , 0
       0      .1       0   461.2    .045       0   476.2      .1       0
Bank Sta=461.2,476.2
XS Rating Curve= 0 ,0
Exp/Cntr=0.3,0.1

Type RM Length L Ch R = 1 ,50033.9 ,411.069,400,387.732
XS GIS Cut Line= 3
     1834824.067      347168.258     1835061.168       346781.87
     1835330.853       346359.78
#Sta/Elev= 30
       0 1514.09    86.8 1487.21    96.5 1486.51   115.7 1481.16   144.7 1475.18
   173.6 1465.95   192.9 1463.15   212.2 1456.75   241.1 1450.42   270.1 1441.92
   279.7 1440.95   327.9 1430.69   385.8 1411.94     434 1408.96   445.8 1410.12
   460.8 1413.46   482.8 1415.31   551.5 1415.18     581 1417.68   620.3 1426.04
   649.8 1429.82   728.3 1443.95   806.9 1453.73   846.2  1461.7   865.8 1467.92
   885.5 1472.48   914.9 1483.83   924.8 1487.04   934.6 1488.45   954.2 1497.35
#Mann= 3 , 0 , 0
       0      .1       0   445.8    .045       0   460.8      .1       0
Bank Sta=445.8,460.8
XS Rating Curve= 0 ,0
Exp/Cntr=0.3,0.1

Type RM Length L Ch R = 1 ,49633.9 ,450.682,450.526,451.536
XS GIS Cut Line= 3
     1835348.747      347428.623     1835388.376      346982.805
     1835421.415      346366.488
#Sta/Elev= 30
       0 1538.62    38.9  1529.1    68.1 1519.36    77.8 1517.82    97.3 1509.86
     107 1508.52   136.2 1497.77   155.7 1493.05   175.1 1485.47   194.6 1481.12
   223.8 1470.24     253 1461.95   350.3  1442.5   379.5  1430.5   408.7 1413.53
   440.1  1408.5   455.1 1407.11   457.4 1407.05   486.8 1413.65   604.3 1415.24
   653.3 1424.77     859 1446.93   947.2 1461.73   966.8  1469.1   976.6 1470.42
   996.2 1478.08  1015.8 1482.63  1045.2 1494.81    1055 1495.96  1064.8 1499.66
#Mann= 3 , 0 , 0
       0      .1       0   440.1    .045       0   455.1      .1       0
Bank Sta=440.1,455.1
XS Rating Curve= 0 ,0
Exp/Cntr=0.3,0.1

Type RM Length L Ch R = 1 ,49183.4 ,373.725,377.873,379.088
XS GIS Cut Line= 3
     1835793.724      347406.272     1835796.766      346896.421
     1835827.266      346171.948
#Sta/Elev= 30
       0 1512.17    19.6 1506.44    39.2  1497.6    58.8 1492.83    78.4  1485.1
    98.1 1480.15   117.7 1473.15   137.3 1469.36   176.5 1458.71   196.1 1451.82
   215.7 1448.09   264.7 1434.81   343.2 1420.58   431.4  1407.6   460.8 1405.13
   503.5 1404.99   518.5 1404.94   539.3 1404.58   558.9 1406.21   588.3 1416.32
   627.4 1422.98     794 1439.05   862.6 1451.97   960.6 1465.79   980.2 1470.93
     990 1471.38  1058.6 1489.27  1068.4 1489.88    1137 1507.99    1235 1522.91
#Mann= 3 , 0 , 0
       0      .1       0   503.5    .045       0   518.5      .1       0
Bank Sta=503.5,518.5
XS Rating Curve= 0 ,0
Exp/Cntr=0.3,0.1

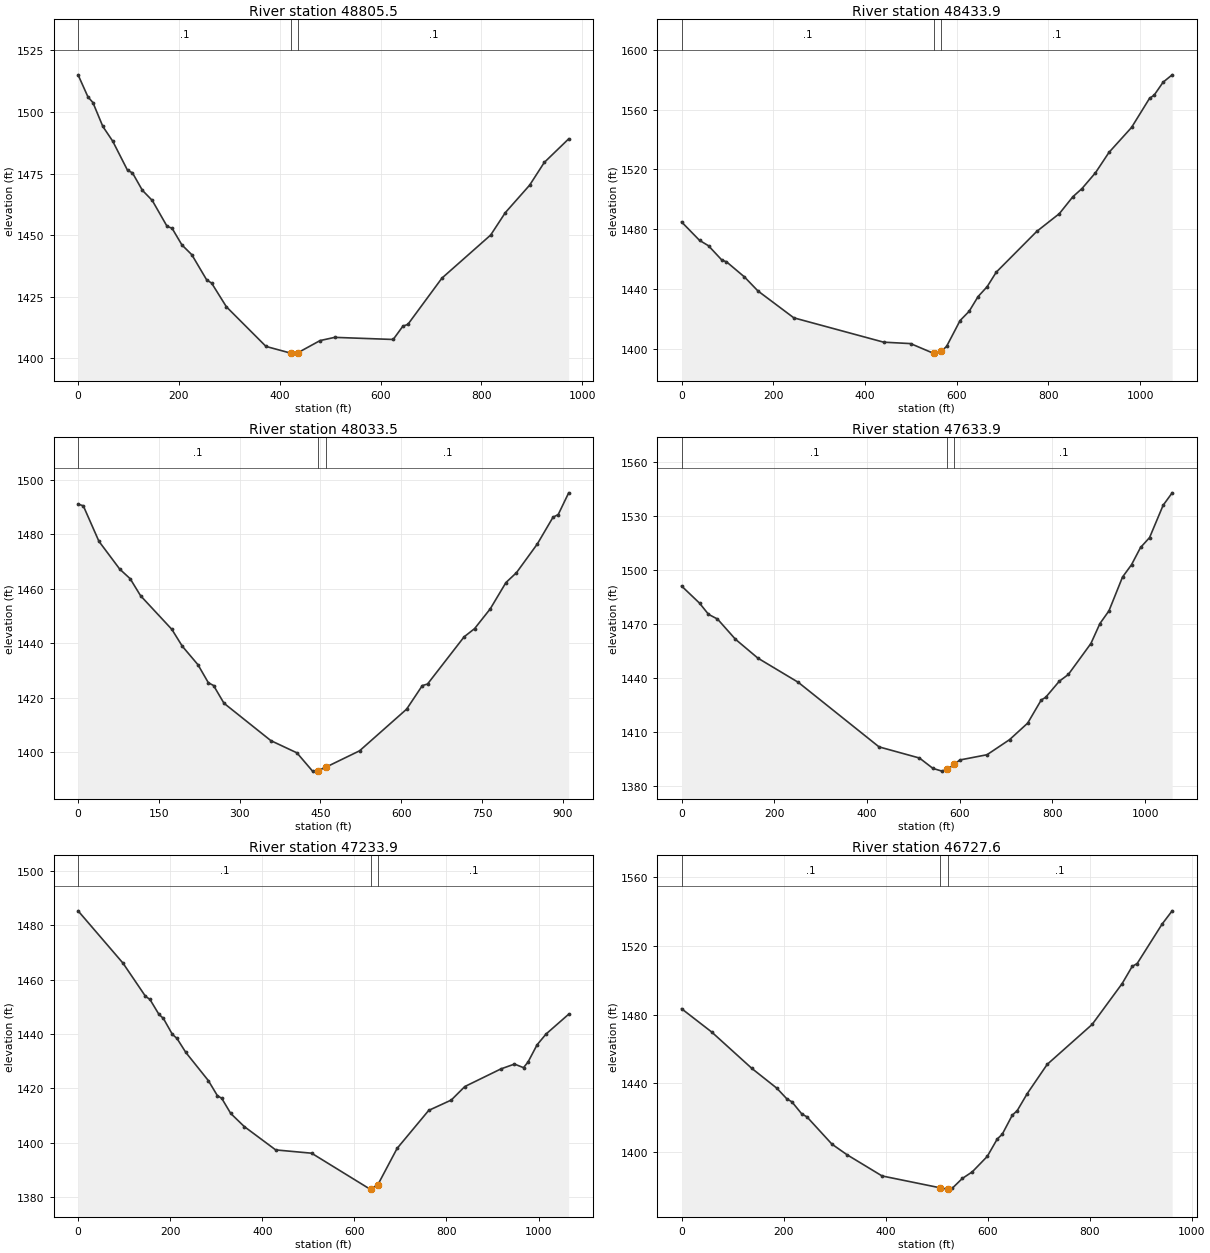
Type RM Length L Ch R = 1 ,48805.5 ,372.267,371.601,373.826
XS GIS Cut Line= 3
     1836061.389      347456.042     1836143.992      347022.375
     1836095.831      346492.856
#Sta/Elev= 30
       0 1515.07    19.6 1506.11    29.4 1503.83    49.1 1494.13    68.7 1488.15
    98.1 1476.33   107.9 1475.28   127.5 1468.22   147.2 1464.07   176.6 1453.55
   186.4 1452.81     206 1446.03   225.6 1442.06   255.1 1431.84   264.9 1430.54
   294.3  1420.9   372.8 1404.83   421.7 1402.11   436.7 1402.35   480.1 1407.21
   509.1 1408.51   625.1 1407.65   644.5  1413.1   654.1 1413.74   721.8 1432.56
   818.5 1450.05   847.5 1459.13   895.8  1470.3   924.8 1479.51   973.2 1489.08
#Mann= 3 , 0 , 0
       0      .1       0   421.7    .045       0   436.7      .1       0
Bank Sta=421.7,436.7
XS Rating Curve= 0 ,0
Exp/Cntr=0.3,0.1

Type RM Length L Ch R = 1 ,48433.9 ,399.695,400.408,399.47
XS GIS Cut Line= 3
     1836306.908      347446.522     1836438.562      346904.098
     1836558.469      346406.738
#Sta/Elev= 30
       0 1484.91    39.2 1472.59    58.8 1468.97    88.1 1459.34    97.9 1458.28
   137.1 1448.16   166.5  1438.8   244.8 1420.82   440.7 1404.56   499.4 1403.61
   548.4 1397.24   550.7 1397.29   565.7 1398.35   577.8 1401.67   607.4 1419.03
     627 1425.16   646.7 1435.07   666.4 1441.64   686.1 1451.29   774.6 1478.59
   823.8 1490.44   853.3 1501.74     873 1507.15   902.5 1517.72     932 1531.35
   981.2 1548.02  1020.6 1567.56  1030.4 1569.56  1050.1 1578.29  1069.8 1583.19
#Mann= 3 , 0 , 0
       0      .1       0   550.7    .045       0   565.7      .1       0
Bank Sta=550.7,565.7
XS Rating Curve= 0 ,0
Exp/Cntr=0.3,0.1

Type RM Length L Ch R = 1 ,48033.5 ,378.967,399.592,408.256
XS GIS Cut Line= 3
     1836655.886      347557.581     1836740.762      347110.792
      1836819.14      346661.322
#Sta/Elev= 30
       0 1490.98     9.7 1490.36    38.7 1477.36    77.4 1467.14    96.8 1463.62
   116.1 1457.38   174.2 1445.04   193.5 1438.89   222.6  1432.1   241.9 1425.49
   251.6 1424.47   270.9 1417.98     358 1404.26   406.4 1399.78   435.4 1393.08
   446.1  1393.3   461.1 1394.62   522.7 1400.53   610.1 1415.81   639.2 1424.44
   648.9 1425.01   716.9 1442.33   736.3 1445.33   765.4 1452.59   794.5 1462.22
     814 1465.83   852.8 1476.37   881.9 1486.17   891.6 1487.16     911 1495.12
#Mann= 3 , 0 , 0
       0      .1       0   446.1    .045       0   461.1      .1       0
Bank Sta=446.1,461.1
XS Rating Curve= 0 ,0
Exp/Cntr=0.3,0.1

Type RM Length L Ch R = 1 ,47633.9 ,395.888,400,410.144
XS GIS Cut Line= 3
     1836722.047      347600.929     1837123.576      347181.055
     1837339.984      346755.568
#Sta/Elev= 30
       0 1491.07    38.7 1481.57    58.1 1475.35    77.5 1472.73   116.2 1461.51
   164.6 1451.03   251.8 1437.58     426 1401.74   513.2 1395.55   542.2 1389.81
   561.6 1388.28   573.5 1389.23   588.5 1392.15   600.4 1394.47   658.9 1397.38
   707.6 1405.77   746.6 1414.93   775.8 1427.75   785.5 1429.27   814.8 1438.18
   834.3 1441.94     883 1459.13   902.5 1470.23   921.9 1477.25   951.2 1496.03
   970.6 1502.88   990.1 1512.46  1009.6 1517.97  1038.8 1535.89  1058.3  1542.8
#Mann= 3 , 0 , 0
       0      .1       0   573.5    .045       0   588.5      .1       0
Bank Sta=573.5,588.5
XS Rating Curve= 0 ,0
Exp/Cntr=0.3,0.1

Type RM Length L Ch R = 1 ,47233.9 ,491.342,506.371,530.026
XS GIS Cut Line= 3
     1836786.919      347681.118      1837393.18      347464.546
      1837737.45      347221.038
#Sta/Elev= 30
       0 1485.31    97.5 1466.06   146.3 1453.86   156.1 1452.68   175.6 1447.19
   185.3 1445.69   204.8 1439.82   214.6 1438.37   234.1 1433.15   282.9  1422.8
   302.4  1417.3   312.1 1416.24   331.6 1410.69   360.9 1405.88   429.2 1397.27
   507.2 1396.06     634 1382.83   636.3 1382.88   651.3 1384.52   692.8 1397.81
   761.5 1411.82   810.5 1415.63   839.9  1420.6   918.4  1427.1   947.8 1428.88
   967.4 1427.56   977.2 1429.63   996.8 1435.95  1016.4 1439.95  1065.5 1447.24
#Mann= 3 , 0 , 0
       0      .1       0   636.3    .045       0   651.3      .1       0
Bank Sta=636.3,651.3
XS Rating Curve= 0 ,0
Exp/Cntr=0.3,0.1

Type RM Length L Ch R = 1 ,46727.6 ,286.886,293.629,296.827
XS GIS Cut Line= 3
     1836784.836      347774.867     1837277.408      347911.175
     1837693.405      348084.661
#Sta/Elev= 30
       0 1483.43      59 1469.88   137.6 1448.73   186.7 1437.18   206.4 1430.96
   216.2 1429.25   235.9 1422.11   245.7  1420.5   294.9 1404.56   324.3 1398.44
   393.1 1386.07   507.6 1379.13   520.9  1378.4   522.6 1378.48   530.7 1378.91
   550.3 1384.59   569.9 1388.45   599.3 1397.44   618.9 1407.59   628.7 1410.35
   648.3 1421.42   658.1 1424.12   677.7 1434.01   716.8 1451.02     805  1474.3
   863.8 1498.09   883.4 1508.04   893.2 1509.73   942.2 1532.75   961.8 1540.41
#Mann= 3 , 0 , 0
       0      .1       0   507.6    .045       0   522.6      .1       0
Bank Sta=507.6,522.6
XS Rating Curve= 0 ,0
Exp/Cntr=0.3,0.1