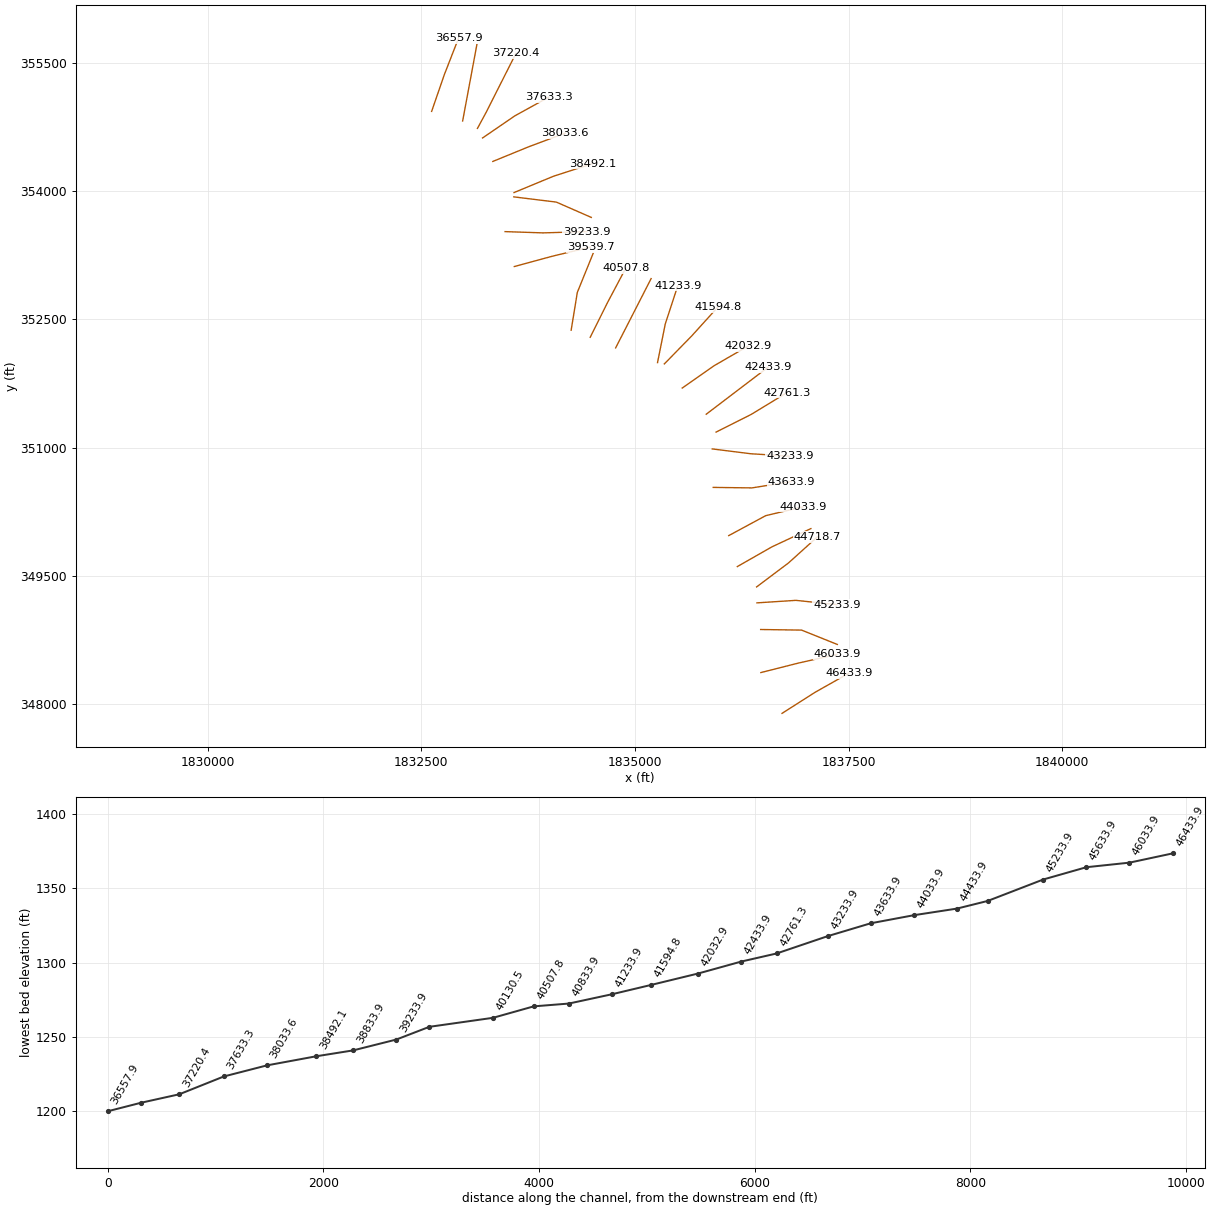
HEC-RAS study WhtdyCrk.prj: WhtdyCrk

--- WhtdyCrk.g01 (geometry) --- (continued)

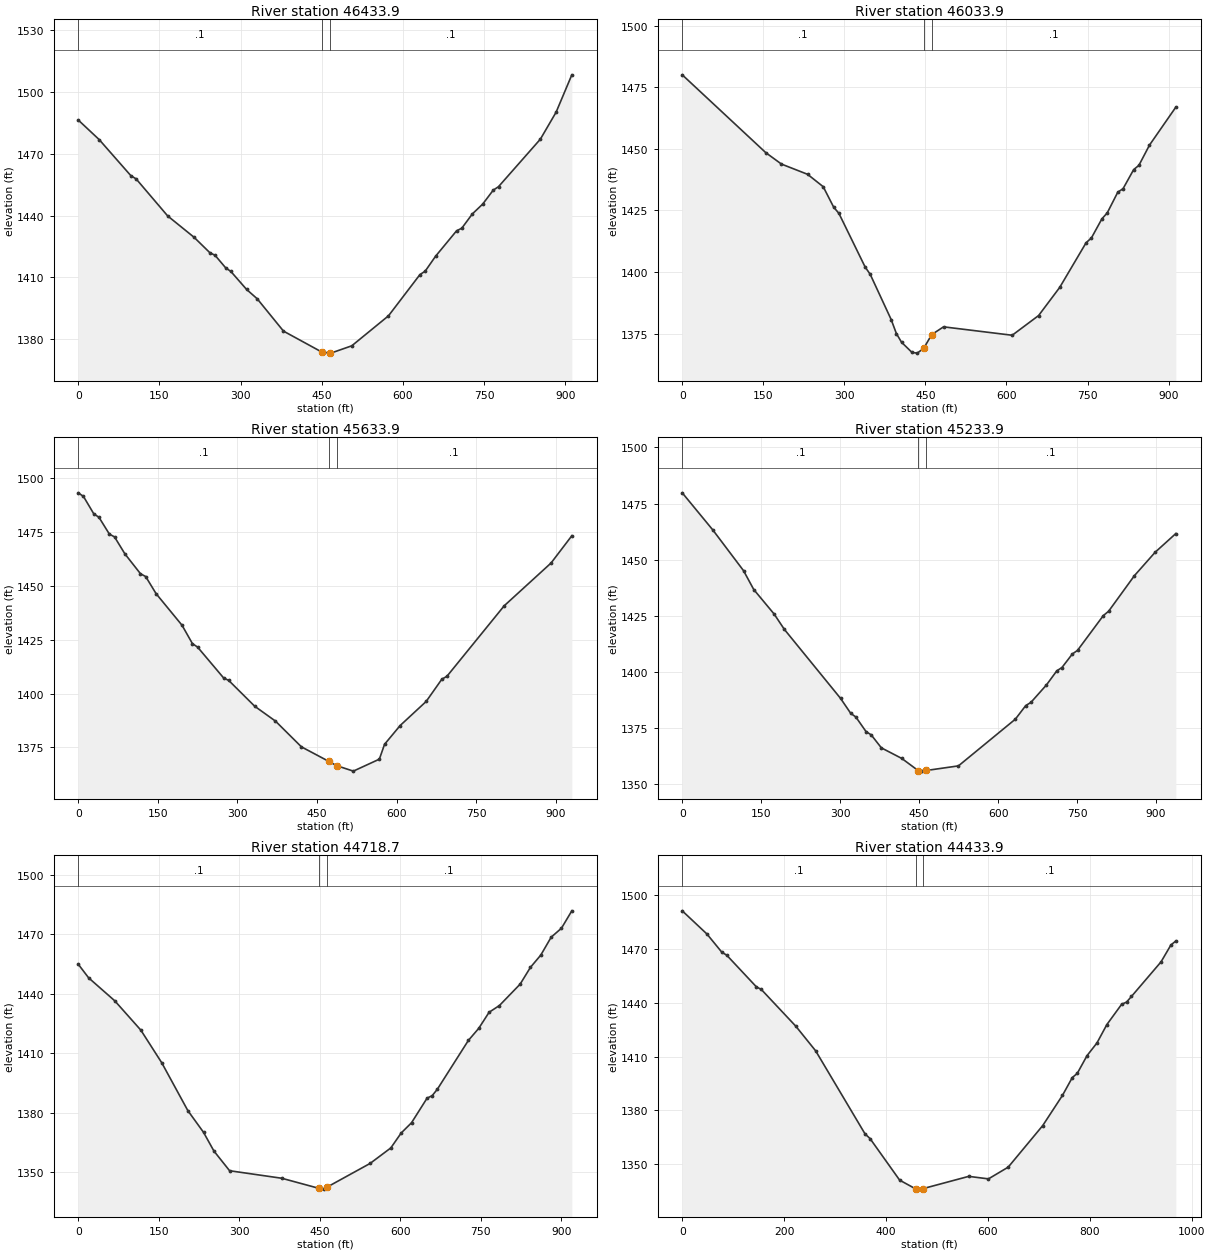
Type RM Length L Ch R = 1 ,46433.9 ,407.227,400,393.382
XS GIS Cut Line= 3
     1836721.178      347892.345       1837106.7      348137.992
     1837502.901      348361.632
#Sta/Elev= 30
       0 1486.48    38.9 1476.91    97.3 1459.42     107 1457.87   165.3 1439.87
     214 1429.52   243.2 1422.02   252.9 1420.74   272.3 1414.71   282.1 1412.89
   311.2 1404.15   330.7 1399.64   379.3 1383.92   449.6 1373.83   464.6 1373.26
   466.8 1373.23   505.5 1376.79   573.3 1391.35   631.4 1411.37   641.1 1413.04
   660.4 1420.32   699.1 1432.64   708.8 1433.92   728.2 1440.83   747.5 1445.66
   766.9 1452.41   776.6 1454.08     854 1477.18   883.1  1490.3   912.1 1508.42
#Mann= 3 , 0 , 0
       0      .1       0   449.6    .045       0   464.6      .1       0
Bank Sta=449.6,464.6
XS Rating Curve= 0 ,0
Exp/Cntr=0.3,0.1

Type RM Length L Ch R = 1 ,46033.9 ,405.697,400,386.254
XS GIS Cut Line= 3
     1836473.779      348369.559     1836914.184      348480.819
     1837362.325      348581.439
#Sta/Elev= 30
       0 1480.09   154.6 1448.47   183.6 1443.83     232 1439.67   260.9 1434.63
   280.3  1426.3   289.9 1423.82   338.3 1402.08   347.9 1399.02   386.6 1380.69
   396.3 1374.98   405.9 1371.43   425.2 1367.31   434.9 1367.03   446.7 1368.93
   461.7 1374.57   483.6 1377.71   610.6 1374.29   659.5  1382.3   698.5 1393.71
   747.4 1411.88   757.2 1413.82   776.7 1421.61   786.5 1423.99     806  1432.4
   815.8 1433.84   835.4 1441.58   845.1 1443.32   864.7 1451.54   913.5 1466.98
#Mann= 3 , 0 , 0
       0      .1       0   446.7    .045       0   461.7      .1       0
Bank Sta=446.7,461.7
XS Rating Curve= 0 ,0
Exp/Cntr=0.3,0.1

Type RM Length L Ch R = 1 ,45633.9 ,395.233,400,407.844
XS GIS Cut Line= 3
      1836470.91      348873.236     1836949.985      348866.157
     1837368.373      348698.459
#Sta/Elev= 30
       0 1493.32     9.8 1491.67    29.3 1483.57    39.1 1481.93    58.7 1474.13
    68.4 1472.84      88 1464.92   117.3 1455.71   127.1  1454.4   146.7 1446.45
   195.6 1431.75   215.1 1423.24   224.9  1421.6   273.8  1407.3   283.6  1406.1
   332.5 1394.12   371.6 1387.21   420.5 1375.24   471.6 1368.55   486.6 1366.53
   518.3 1363.96   567.3 1369.52   577.1 1376.43   606.5 1385.16   655.5 1396.35
   684.9 1406.65   694.7 1408.07   802.5 1440.81   890.7 1460.68   929.9 1473.36
#Mann= 3 , 0 , 0
       0      .1       0   471.6    .045       0   486.6      .1       0
Bank Sta=471.6,486.6
XS Rating Curve= 0 ,0
Exp/Cntr=0.3,0.1

Type RM Length L Ch R = 1 ,45233.9 ,500.974,515.242,534.36
XS GIS Cut Line= 3
     1836428.391      349184.701     1836883.228      349214.024
      1837362.31      349163.947
#Sta/Elev= 30
       0 1479.76    58.2 1463.17   116.4 1445.06   135.8 1436.66   174.6 1425.71
   193.9  1418.9   300.6 1388.16     320 1381.47   329.7 1379.84   349.1 1373.32
   358.8 1371.89   378.2 1366.08     417 1361.36   448.3 1355.92   455.8 1355.71
   463.3 1355.99   524.6 1358.05   632.7 1378.88   652.4 1384.93   662.2 1386.34
   691.7 1394.12   711.4 1400.42   721.2  1401.9   740.9 1407.93   750.7 1409.53
   799.8 1425.06   809.7 1426.95   858.8 1442.84   898.2 1453.28   937.5 1461.62
#Mann= 3 , 0 , 0
       0      .1       0   448.3    .045       0   463.3      .1       0
Bank Sta=448.3,463.3
XS Rating Curve= 0 ,0
Exp/Cntr=0.3,0.1

Type RM Length L Ch R = 1 ,44718.7 ,287.644,284.758,277.042
XS GIS Cut Line= 3
     1836423.757      349371.074     1836796.815      349651.516
     1837133.317      349954.463
#Sta/Elev= 30
       0 1454.94    19.4 1448.04    68.1 1436.43   116.7 1421.61   155.6 1405.14
   204.2 1380.98   233.4 1370.02   252.8 1360.56     282 1350.61   379.2 1346.81
   447.8 1341.76     457 1341.32   462.8 1342.23   543.8 1354.31   582.3 1362.13
   601.6 1369.66   620.9 1374.85   649.8 1387.25   659.4 1388.55     669 1391.78
   726.8 1416.44   746.1 1422.53   765.4 1430.66   784.6 1434.05   823.2 1444.86
   842.4 1453.34   861.7 1459.54     881 1468.57   900.2 1473.11   919.5 1481.89
#Mann= 3 , 0 , 0
       0      .1       0   447.8    .045       0   462.8      .1       0
Bank Sta=447.8,462.8
XS Rating Curve= 0 ,0
Exp/Cntr=0.3,0.1

Type RM Length L Ch R = 1 ,44433.9 ,397.999,400,395.626
XS GIS Cut Line= 3
     1836198.213       349609.21      1836602.83      349839.583
     1837058.723       350053.02
#Sta/Elev= 30
       0 1491.21    48.5 1478.29    77.6 1468.19    87.3  1466.5   145.5 1448.87
   155.2 1447.41   223.1 1426.89   261.9 1413.22   358.9 1366.92   368.6 1364.38
   426.8 1341.19   458.1 1336.34   465.6 1336.19   473.1  1336.5   562.4  1343.3
   601.1  1341.9   639.9 1348.44   707.6 1371.57   746.3 1388.36   765.7 1398.33
   775.4 1400.64   794.7 1410.57   814.1 1417.61   833.5 1427.82   862.5 1439.13
   872.2 1440.37   881.9 1443.53   939.9 1462.78   959.3 1472.19     969 1474.42
#Mann= 3 , 0 , 0
       0      .1       0   458.1    .045       0   473.1      .1       0
Bank Sta=458.1,473.1
XS Rating Curve= 0 ,0
Exp/Cntr=0.3,0.1

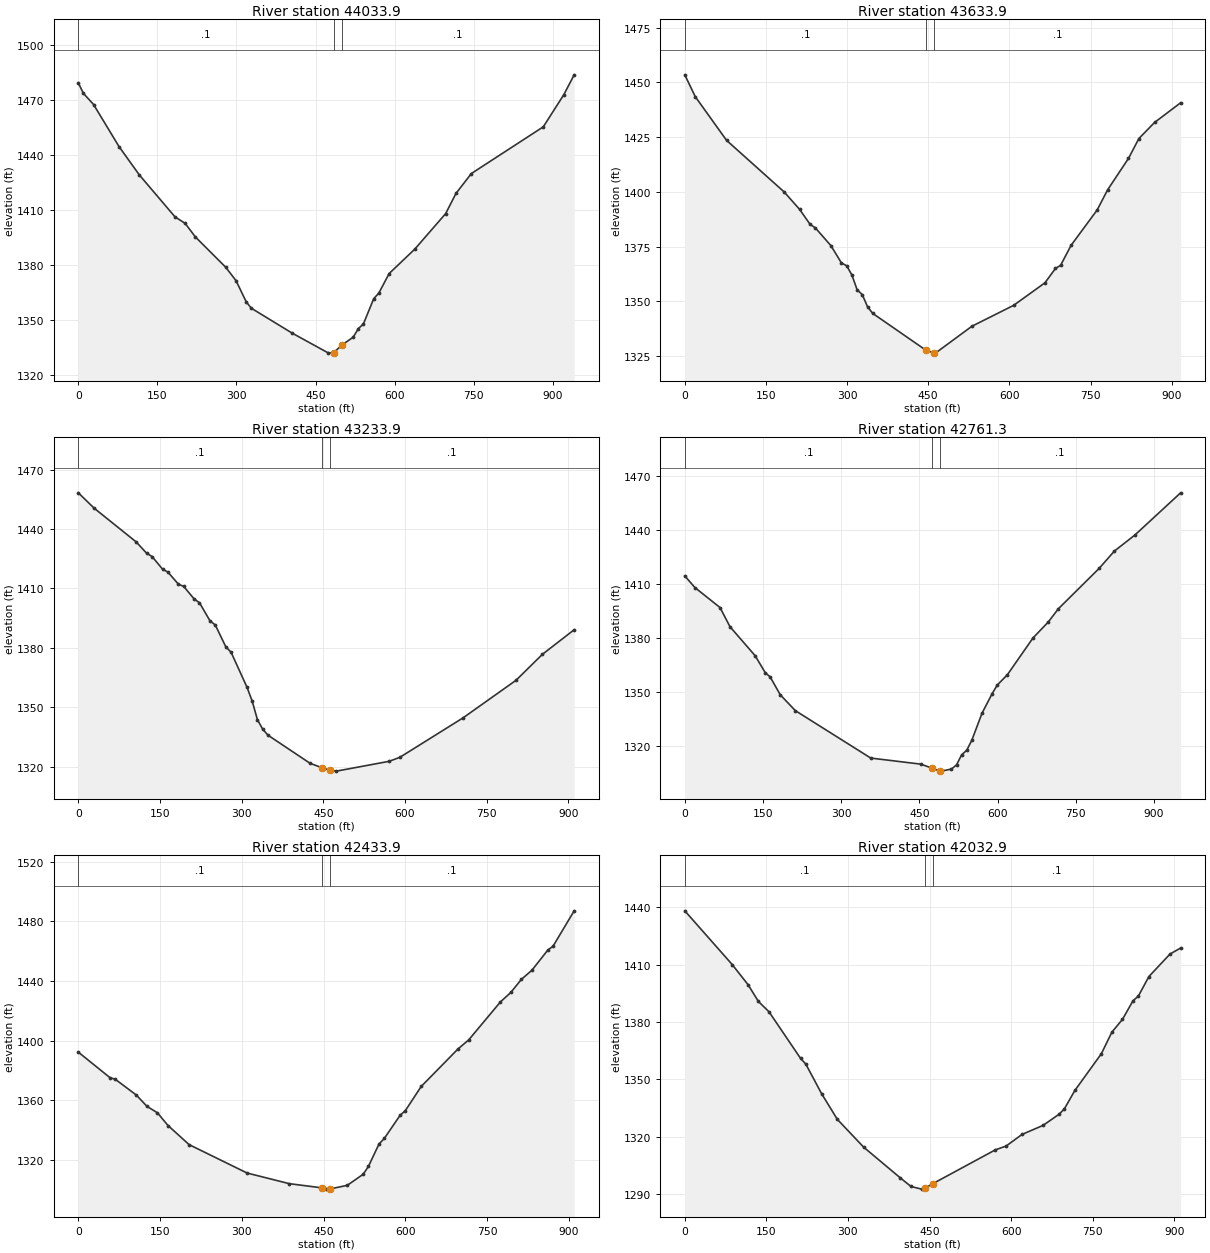
Type RM Length L Ch R = 1 ,44033.9 ,411.504,400,398.62
XS GIS Cut Line= 3
     1836096.982      349970.939     1836530.147      350204.409
     1836966.481      350307.949
#Sta/Elev= 30
       0 1479.13     9.6 1473.48    28.9 1467.37    77.2 1444.42   115.8 1428.92
   183.3  1406.1   202.6 1402.54   221.9 1395.17   279.8 1378.53   299.1 1371.29
   318.4 1359.77   328.1 1356.25   405.2 1342.73   472.8 1332.05   482.4 1331.75
   484.6 1332.06   499.6 1336.06   521.3 1340.45   531.1 1345.06   540.8 1347.71
   560.3 1361.44   570.1 1364.54   589.6 1375.18   638.3 1388.51   696.8 1407.88
   716.3 1418.86   745.5 1429.71     882 1455.21     921 1472.78   940.5 1483.56
#Mann= 3 , 0 , 0
       0      .1       0   484.6    .045       0   499.6      .1       0
Bank Sta=484.6,499.6
XS Rating Curve= 0 ,0
Exp/Cntr=0.3,0.1

Type RM Length L Ch R = 1 ,43633.9 ,402.52,400,394.978
XS GIS Cut Line= 3
     1835915.967      350534.914     1836369.535      350529.099
     1836826.599      350602.367
#Sta/Elev= 30
       0 1453.42    19.3 1443.48    77.2  1423.5   183.4    1400   212.3 1391.96
   231.6 1385.14   241.3 1383.54   270.2 1375.38   289.5 1367.53   299.2 1366.22
   308.8 1362.05   318.5 1355.31   328.1 1353.02   337.8 1347.49   347.4 1344.47
   446.1 1327.59   461.1 1326.37   463.2 1326.33   530.8 1338.62   607.9 1348.16
   665.8 1358.46   685.1 1364.99   694.7 1366.44     714 1375.55   762.2 1391.69
   781.5 1400.88   820.1 1415.25   839.4 1424.34   868.3 1431.66   916.5 1440.66
#Mann= 3 , 0 , 0
       0      .1       0   446.1    .045       0   461.1      .1       0
Bank Sta=446.1,461.1
XS Rating Curve= 0 ,0
Exp/Cntr=0.3,0.1

Type RM Length L Ch R = 1 ,43233.9 ,456.968,472.63,487.517
XS GIS Cut Line= 3
     1835904.503       350984.84     1836355.802      350928.428
     1836810.994      350900.117
#Sta/Elev= 30
       0 1458.35      29  1450.6   106.4 1433.51   125.8 1427.71   135.5 1426.16
   154.8 1419.73   164.5 1418.31   183.9 1412.16   193.5 1411.07   212.9 1404.65
   222.6 1402.79   241.9 1393.63   251.6 1391.56     271 1380.47   280.6 1377.78
   309.7 1360.19   319.3 1353.16     329  1343.7   338.7 1338.88   348.4 1335.84
   425.8 1321.61   447.3 1319.43   462.3 1318.12   474.2 1317.67   571.3 1322.65
   590.7 1324.65   707.1 1344.65   804.1 1363.59   852.7 1376.74   910.9 1389.14
#Mann= 3 , 0 , 0
       0      .1       0   447.3    .045       0   462.3      .1       0
Bank Sta=447.3,462.3
XS Rating Curve= 0 ,0
Exp/Cntr=0.3,0.1

Type RM Length L Ch R = 1 ,42761.3 ,325.152,327.37,328.961
XS GIS Cut Line= 3
     1835948.831      351181.545     1836362.101      351389.381
     1836779.318      351643.078
#Sta/Elev= 30
       0 1414.67    19.3 1408.22    67.5 1397.09    86.7  1386.4   134.9 1370.28
   154.2  1360.9   163.8 1358.44   183.1 1348.53     212 1339.72   356.6 1313.34
     453 1309.94     474 1307.72     489 1306.16   491.9 1306.07   511.4 1307.23
   521.2 1309.56   530.9 1315.12   540.7 1317.69   550.5 1323.27     570 1338.29
   589.5 1349.21   599.3 1353.97   618.8 1359.74   667.7 1380.13     697    1389
   716.5 1396.41   794.6 1418.85   823.9  1428.5     863 1437.36   950.9 1460.89
#Mann= 3 , 0 , 0
       0      .1       0     474    .045       0     489      .1       0
Bank Sta=474,489
XS Rating Curve= 0 ,0
Exp/Cntr=0.3,0.1

Type RM Length L Ch R = 1 ,42433.9 ,402.101,401.028,398.317
XS GIS Cut Line= 3
     1835834.177      351390.901     1836196.431      351666.214
     1836558.685      351941.527
#Sta/Elev= 30
       0 1392.38    58.1 1375.28    67.8 1374.22   106.5 1363.63   125.9 1356.11
   145.2 1351.75   164.6 1343.25   203.3 1330.45   309.8 1311.42   387.2 1304.31
   447.5 1301.48     455 1300.65   462.5  1300.8   493.7 1303.21   522.8 1310.61
   532.4 1315.86   551.8 1330.85   561.5 1334.57   590.5 1350.06   600.2 1353.22
   629.3 1369.41     697 1394.58   716.4 1400.55   774.5 1425.94   793.8 1432.37
   813.2 1441.13   832.6 1447.28   861.6  1460.7   871.3 1463.34     910 1487.01
#Mann= 3 , 0 , 0
       0      .1       0   447.5    .045       0   462.5      .1       0
Bank Sta=447.5,462.5
XS Rating Curve= 0 ,0
Exp/Cntr=0.3,0.1

Type RM Length L Ch R = 1 ,42032.9 ,433.776,438.109,444.368
XS GIS Cut Line= 3
     1835552.653      351696.534     1835925.065      351957.295
      1836320.95      352185.827
#Sta/Elev= 30
       0 1438.22    87.1 1410.13   116.1 1399.66   135.4  1390.8   154.8 1385.41
   212.8 1361.05   222.5 1358.04   251.5 1342.57   280.5 1329.11   328.9 1314.57
   396.6 1298.42   415.9 1294.01   435.3 1292.61     441 1293.04     456 1295.46
   571.3  1313.2   590.8 1315.14     620 1321.22   658.9 1325.98     688 1331.75
   697.8 1334.53   717.2 1344.22   765.9 1363.43   785.3 1374.75   804.8 1381.44
   824.2  1391.2   833.9 1393.57   853.4 1403.85   892.3 1415.64   911.7 1418.76
#Mann= 3 , 0 , 0
       0      .1       0     441    .045       0     456      .1       0
Bank Sta=441,456
XS Rating Curve= 0 ,0
Exp/Cntr=0.3,0.1

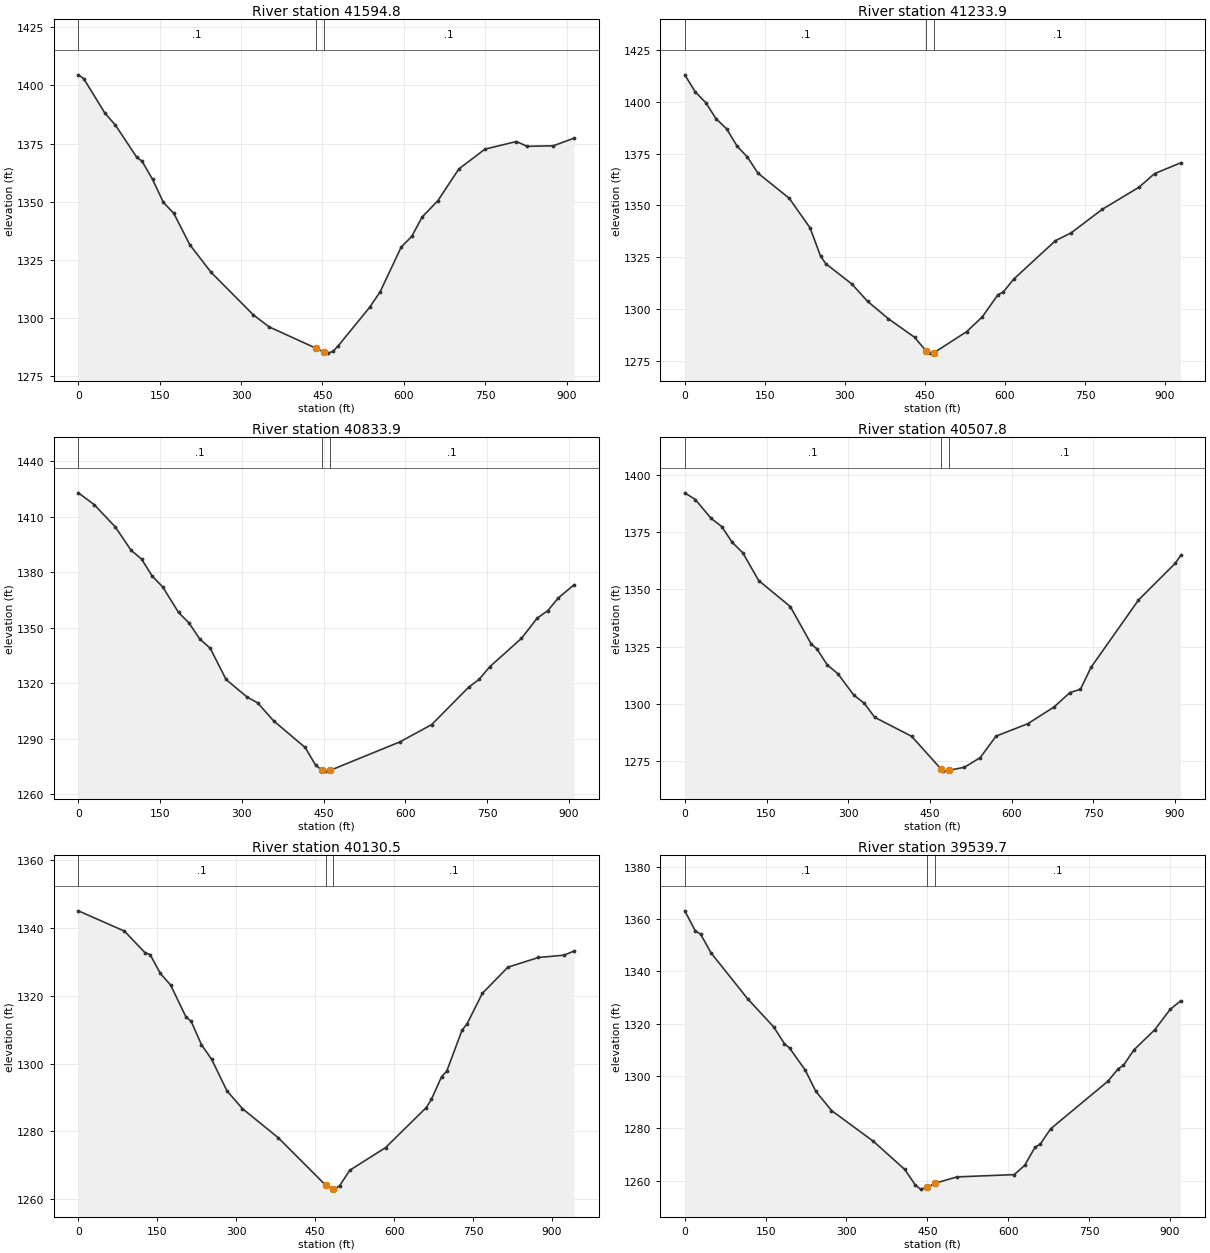
Type RM Length L Ch R = 1 ,41594.8 ,347.425,360.863,371.108
XS GIS Cut Line= 3
     1835343.635      351978.982     1835665.299      352307.648
     1835970.262      352644.159
#Sta/Elev= 30
       0 1404.57     9.8 1402.97    48.9 1388.14    68.5 1382.91   107.6 1369.15
   117.4 1367.45     137 1359.57   156.6  1349.8   176.1 1344.96   205.5 1331.53
   244.6 1319.69   322.9 1301.29   352.2 1296.14   437.4 1287.09   452.4 1285.42
   459.9 1284.91   469.5 1285.66   479.2 1288.09   537.2 1304.67   556.5 1311.34
   595.2 1330.54   614.5 1335.06   633.8 1343.45   662.8 1350.46   701.4  1364.1
   749.8 1372.64   807.7  1375.9   827.1 1373.82   875.4 1374.05     914 1377.34
#Mann= 3 , 0 , 0
       0      .1       0   437.4    .045       0   452.4      .1       0
Bank Sta=437.4,452.4
XS Rating Curve= 0 ,0
Exp/Cntr=0.3,0.1

Type RM Length L Ch R = 1 ,41233.9 ,406.193,400,396.712
XS GIS Cut Line= 3
     1835263.712      351994.315      1835354.14      352445.218
     1835500.306      352891.112
#Sta/Elev= 30
       0 1413.07    19.6 1404.84    39.1 1399.68    58.7 1391.84    78.3 1387.04
    97.8 1378.72   117.4 1373.34     137 1365.63   195.7 1353.47   234.8 1339.16
   254.4 1325.53   264.2 1321.89   313.1 1312.06   342.5 1303.72   381.6 1295.28
   430.5 1286.36   452.4 1279.72   459.9  1278.7   467.4 1278.98   528.3  1289.1
   557.6 1296.25     587 1306.97   596.7  1308.2   616.3 1314.42   694.5 1332.99
   723.8 1336.74   782.5 1348.18   850.9 1358.75   880.2 1365.37   929.1 1370.57
#Mann= 3 , 0 , 0
       0      .1       0   452.4    .045       0   467.4      .1       0
Bank Sta=452.4,467.4
XS Rating Curve= 0 ,0
Exp/Cntr=0.3,0.1

Type RM Length L Ch R = 1 ,40833.9 ,326.436,326.104,325.772
XS GIS Cut Line= 3
     1834773.706      352166.748     1834981.227      352571.668
     1835188.749      352976.587
#Sta/Elev= 30
       0 1422.94      29  1416.6    67.8 1404.51    96.8  1391.9   116.2 1387.07
   135.5 1377.94   154.9 1372.04   183.9 1358.29   203.3 1352.49   222.7 1343.96
     242 1338.93   271.1 1322.03   309.8 1312.49   329.1 1309.38   358.2  1299.7
   416.3 1285.24   435.6 1275.64   447.5  1272.8     455 1272.45   462.5 1272.91
   590.5  1288.3   648.6 1297.64   716.4 1317.83   735.7 1322.12   755.1  1328.9
   813.2 1344.22   842.2 1355.19   861.6 1359.23     881 1366.12     910 1373.27
#Mann= 3 , 0 , 0
       0      .1       0   447.5    .045       0   462.5      .1       0
Bank Sta=447.5,462.5
XS Rating Curve= 0 ,0
Exp/Cntr=0.3,0.1

Type RM Length L Ch R = 1 ,40507.8 ,374.977,377.299,379.62
XS GIS Cut Line= 3
     1834475.744      352290.422     1834679.028      352697.684
     1834892.478      353099.474
#Sta/Elev= 30
       0 1392.27    19.4 1389.33    48.4 1381.07    67.8 1377.52    87.2 1370.56
   106.5 1366.04   135.6 1353.92   193.7 1342.51   232.4 1325.99   242.1 1324.15
   261.5    1317   280.9  1313.2   309.9  1303.9   329.3 1300.26   348.6 1294.11
   416.4 1285.78   470.6 1271.42   474.5 1270.56   485.6 1270.93   513.3 1272.26
   542.3 1276.48   571.3 1285.87   629.4 1291.28   677.8 1298.61   706.9 1304.91
   726.2 1306.35   745.6 1315.94   832.7 1345.37   900.5 1361.51   910.1 1364.89
#Mann= 3 , 0 , 0
       0      .1       0   470.6    .045       0   485.6      .1       0
Bank Sta=470.6,485.6
XS Rating Curve= 0 ,0
Exp/Cntr=0.3,0.1

Type RM Length L Ch R = 1 ,40130.5 ,613.407,590.829,566.955
XS GIS Cut Line= 3
     1834252.741      352373.066     1834324.972      352815.301
     1834510.772      353273.166
#Sta/Elev= 30
       0 1345.12    87.7 1339.12   126.6 1332.76   136.4  1332.2   155.9  1326.6
   175.3 1323.21   204.6 1313.75   214.3 1312.51   233.8 1305.61   253.3 1301.25
   282.5 1291.91   311.7 1286.69   379.9 1278.07   469.8 1264.08   484.8 1262.91
   486.9 1262.88   496.5 1263.89   515.9 1268.46   583.7 1275.14   661.2 1286.98
   670.9  1289.4   690.3 1296.13     700 1297.72   729.1 1309.82   738.8 1311.76
   767.8 1320.75   816.3 1328.47   874.4 1331.33   922.8 1332.01   942.2 1333.25
#Mann= 3 , 0 , 0
       0      .1       0   469.8    .045       0   484.8      .1       0
Bank Sta=469.8,484.8
XS Rating Curve= 0 ,0
Exp/Cntr=0.3,0.1

Type RM Length L Ch R = 1 ,39539.7 ,312.818,305.768,300.534
XS GIS Cut Line= 3
     1833587.886      353117.846     1834038.212      353239.831
     1834479.201      353345.371
#Sta/Elev= 30
       0 1363.14    19.4 1355.51    29.2 1354.27    48.6  1347.1   116.6 1329.54
   165.2 1318.74   184.7 1312.44   194.4 1310.72   223.6 1302.26     243 1294.24
   272.2 1286.86   349.9 1275.11   408.2 1264.33   427.7  1258.4   437.4 1256.83
   449.7 1257.51   464.7  1259.1   505.1  1261.5   611.3 1262.38   630.6  1265.9
   649.9 1272.85   659.5 1274.01   678.8 1279.87   784.9 1298.02   804.2  1302.8
   813.9 1304.11   833.2 1309.98   871.8 1317.66   900.7 1325.52     920 1328.75
#Mann= 3 , 0 , 0
       0      .1       0   449.7    .045       0   464.7      .1       0
Bank Sta=449.7,464.7
XS Rating Curve= 0 ,0
Exp/Cntr=0.3,0.1

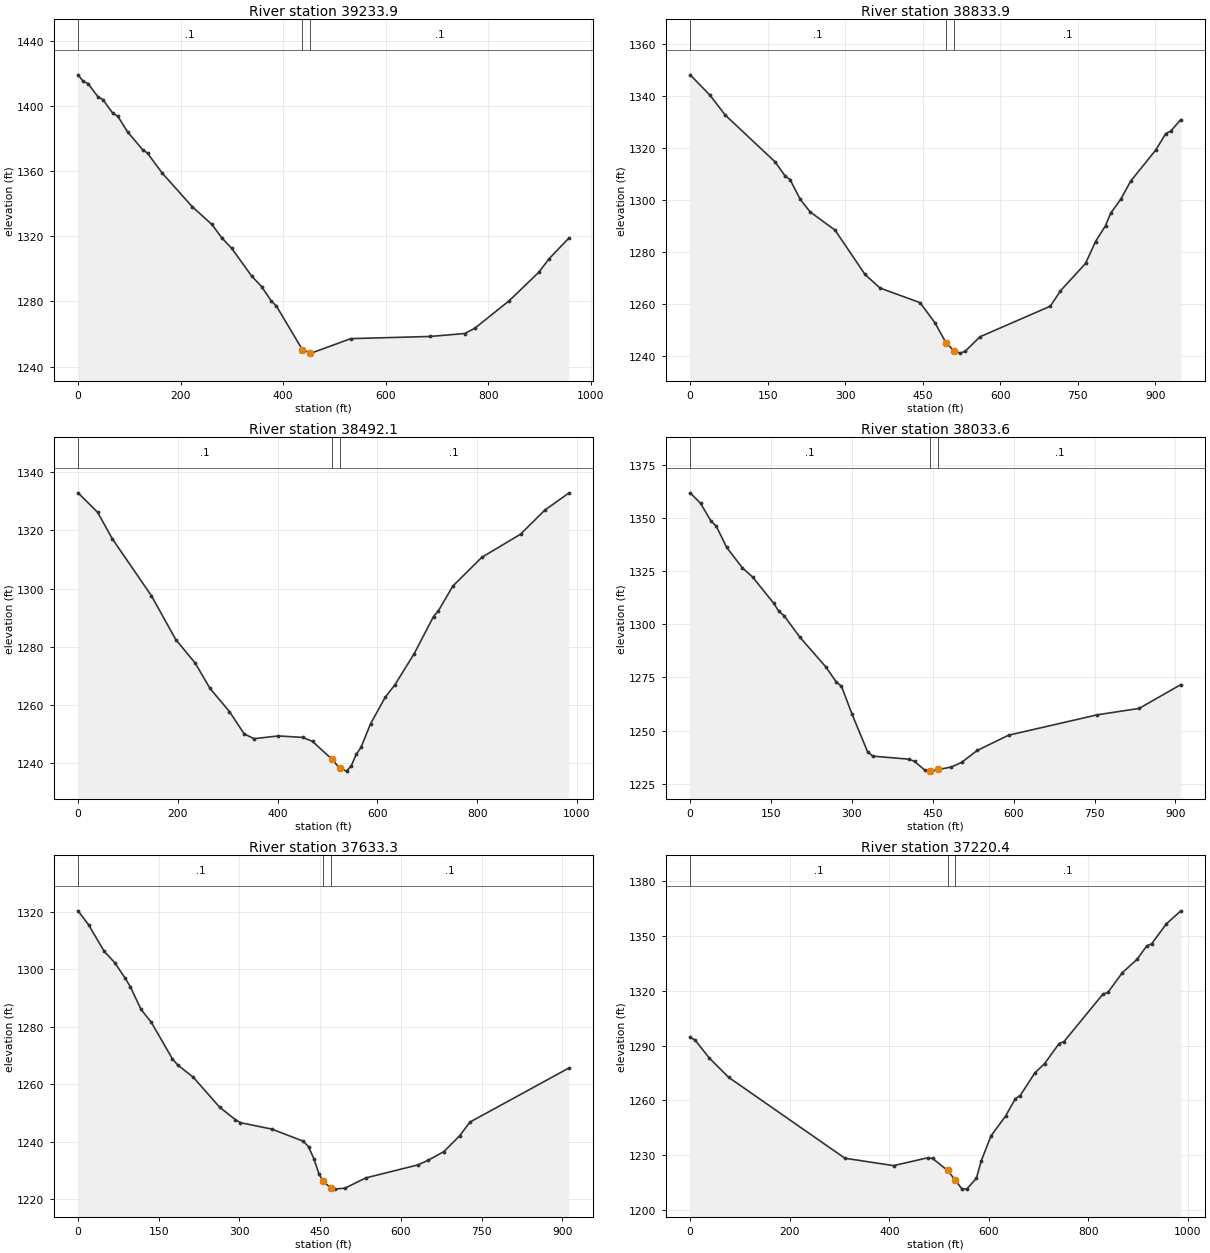
Type RM Length L Ch R = 1 ,39233.9 ,401.901,400,389.963
XS GIS Cut Line= 3
     1833479.069      353526.098     1833923.733      353511.275
     1834435.685      353526.368
#Sta/Elev= 30
       0 1419.02     9.7 1415.12    19.3 1413.64    38.7 1405.63    48.4 1403.83
    67.7 1395.47    77.4 1393.65    96.7 1383.95   125.7 1373.18   135.4 1370.97
   164.4 1358.63   222.5 1338.18   261.1 1327.22   280.5 1318.97   299.8 1312.51
   338.5 1295.62   357.9 1289.13   377.2 1280.15   386.9 1277.14   437.4 1250.46
   452.4 1248.49   454.6  1248.3   531.9 1257.19   686.5 1258.52   754.1 1260.34
   773.5  1263.5   841.1 1280.51   899.1 1298.07   918.4 1306.13   957.1 1318.85
#Mann= 3 , 0 , 0
       0      .1       0   437.4    .045       0   452.4      .1       0
Bank Sta=437.4,452.4
XS Rating Curve= 0 ,0
Exp/Cntr=0.3,0.1

Type RM Length L Ch R = 1 ,38833.9 ,330.871,341.861,359.029
XS GIS Cut Line= 3
     1833580.521      353932.484     1834079.443      353871.254
     1834488.589      353692.253
#Sta/Elev= 30
       0 1348.28    38.7 1340.36    67.7  1332.8   164.3 1314.74   183.7 1309.29
   193.3  1307.9   212.7 1300.38     232 1295.46   280.3 1288.43   338.3 1271.34
   367.3  1266.1   444.7 1260.48   473.7 1252.67   495.2 1244.91   510.2 1242.01
   522.1 1241.02   531.8 1241.69   560.9 1247.34   696.8 1259.12   716.3 1265.03
   764.8 1275.57   784.2 1284.02   803.6 1290.16   813.3 1294.92   832.8 1300.26
   852.2 1307.31   900.7 1319.31   920.1 1325.65   929.8 1326.64   949.3 1331.05
#Mann= 3 , 0 , 0
       0      .1       0   495.2    .045       0   510.2      .1       0
Bank Sta=495.2,510.2
XS Rating Curve= 0 ,0
Exp/Cntr=0.3,0.1

Type RM Length L Ch R = 1 ,38492.1 ,457.188,458.44,459.552
XS GIS Cut Line= 3
     1833584.267      353982.733       1834045.7       354173.56
     1834506.575      354322.271
#Sta/Elev= 30
       0 1332.97    39.2 1326.26    68.5 1317.16   146.9 1297.54   195.8 1282.41
     235 1274.25   264.4 1265.59   303.5 1257.58   332.9 1249.93   352.5 1248.26
   401.4 1249.21   450.4  1248.7     470 1247.31     509 1241.17     524 1238.15
   538.1 1237.08   547.8 1238.99   557.4 1242.81   567.1 1245.29   586.5 1253.49
   615.6 1262.54   634.9  1266.8   673.7 1277.56   712.4 1290.35   722.1 1292.29
   751.2 1300.86   809.3 1310.76   886.8 1318.71   935.2 1326.96   983.6 1332.89
#Mann= 3 , 0 , 0
       0      .1       0     509    .045       0     524      .1       0
Bank Sta=509,524
XS Rating Curve= 0 ,0
Exp/Cntr=0.3,0.1

Type RM Length L Ch R = 1 ,38033.6 ,395.69,400.336,403.829
XS GIS Cut Line= 3
     1833335.854      354346.664     1833757.027      354518.704
     1834183.495      354678.017
#Sta/Elev= 30
       0 1361.73    19.4 1356.76    38.7 1348.45    48.4 1346.09    67.8 1336.08
    96.8 1326.52   116.2 1322.06   154.9 1309.87   164.6 1306.02   174.2 1304.01
   203.3 1293.95   251.7 1279.93     271 1272.84   280.7 1270.83   300.1 1257.82
   329.1 1240.07   338.8 1237.99   406.6 1236.55   416.2  1235.5   435.6 1231.35
   445.3 1230.95   445.4 1230.95   460.4 1231.73     484 1232.84   503.4 1235.03
   532.4 1240.67   590.6 1247.83   755.2 1257.42   832.7 1260.41   910.2 1271.63
#Mann= 3 , 0 , 0
       0      .1       0   445.4    .045       0   460.4      .1       0
Bank Sta=445.4,460.4
XS Rating Curve= 0 ,0
Exp/Cntr=0.3,0.1

Type RM Length L Ch R = 1 ,37633.3 ,399.366,412.884,427.77
XS GIS Cut Line= 3
     1833215.603      354621.189     1833593.242      354879.569
     1833991.321      355098.989
#Sta/Elev= 30
       0  1320.3    19.5 1315.44    48.7 1306.16    68.1 1302.29    87.6 1296.84
    97.4 1293.82   116.8 1286.06   136.3 1281.46   175.2 1268.86     185 1266.72
   214.2 1262.41   262.9 1252.04   292.1 1247.69   301.8 1246.62   360.2 1244.38
   418.6 1240.17   428.4 1238.24   438.1 1234.15   447.8 1228.79     455 1226.37
     470 1223.83   476.9  1223.5   496.3 1223.86   534.9 1227.42   631.7 1231.93
     651 1233.56     680 1236.58     709 1242.01   728.4 1246.83   912.1 1265.61
#Mann= 3 , 0 , 0
       0      .1       0     455    .045       0     470      .1       0
Bank Sta=455,470
XS Rating Curve= 0 ,0
Exp/Cntr=0.3,0.1

Type RM Length L Ch R = 1 ,37220.4 ,348.142,355.225,362.308
XS GIS Cut Line= 3
     1833156.127       354733.39     1833257.606      354920.735
     1833606.277       355610.27
#Sta/Elev= 30
       0 1294.47     9.7  1293.1    38.7  1283.1    77.5 1272.61   310.9 1228.43
   408.7  1224.4   477.1 1228.68   486.9 1228.32   517.2 1221.74   532.2 1216.59
   545.6 1211.77   555.4 1211.55     575  1217.5   584.7 1227.02   604.3 1240.67
   633.6 1251.49   653.2    1261     663 1262.71   692.3 1275.03   711.9 1280.15
   741.2 1291.13     751 1292.21   829.2 1318.15     839 1319.01   868.4 1329.91
   897.7 1337.15   917.3 1344.54   927.1 1345.65   956.4  1356.5   985.7 1363.64
#Mann= 3 , 0 , 0
       0      .1       0   517.2    .045       0   532.2      .1       0
Bank Sta=517.2,532.2
XS Rating Curve= 0 ,0
Exp/Cntr=0.3,0.1

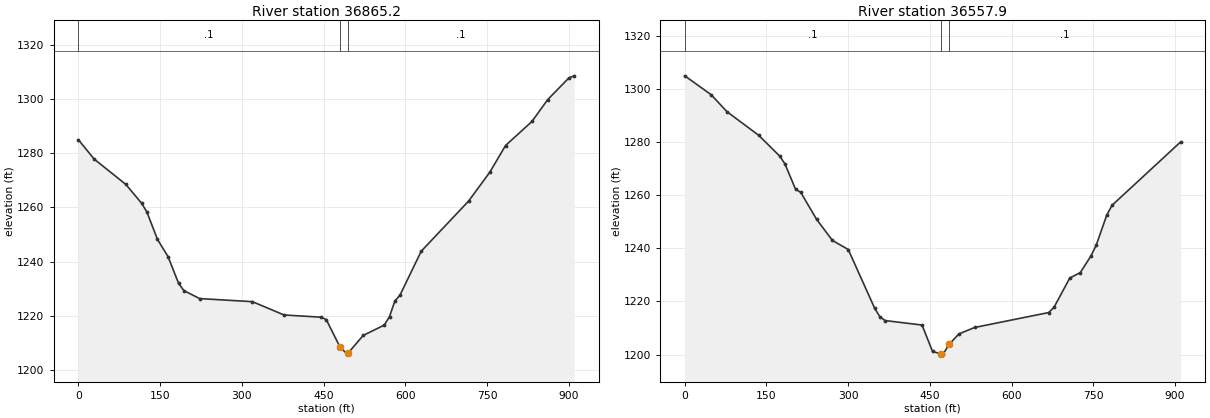
Type RM Length L Ch R = 1 ,36865.2 ,311.513,307.281,303.049
XS GIS Cut Line= 3
     1832982.574      354819.863     1833066.007      355267.148
     1833149.439      355714.433
#Sta/Elev= 30
       0 1284.93      29 1277.78    87.1 1268.45   116.2 1261.47   125.9 1258.23
   145.2 1248.18   164.6 1241.83   183.9 1232.01   193.6 1229.29   222.7 1226.34
   319.5  1225.2   377.6 1220.29   445.3 1219.48     455 1218.61   480.4 1208.41
   493.7 1205.86   495.4  1206.3   522.8 1212.75   561.5 1216.56   571.2 1219.73
   580.9 1225.41   590.5 1227.67   629.3  1243.8   716.4 1262.32   755.1 1272.91
   784.1 1282.78   832.6 1291.66   861.6 1299.74   900.3  1307.7     910 1308.47
#Mann= 3 , 0 , 0
       0      .1       0   480.4    .045       0   495.4      .1       0
Bank Sta=480.4,495.4
XS Rating Curve= 0 ,0
Exp/Cntr=0.3,0.1

Type RM Length L Ch R = 1 ,36557.9 ,643.165,631.87,620.456
XS GIS Cut Line= 3
      1832619.65      354932.175     1832768.279      355362.135
     1832933.948      355786.365
#Sta/Elev= 30
       0 1304.87    48.4 1297.76    77.4 1291.38   135.5 1282.53   174.2 1274.69
   183.9 1271.73   203.3 1262.22   212.9 1261.03     242 1250.88     271 1242.95
   300.1 1239.53   348.5 1217.48   358.1 1214.25   367.8  1212.8   435.6 1211.11
   454.9 1201.16   470.6 1200.26   474.3 1200.17   485.6 1203.92   503.4 1207.78
   532.4 1210.21   668.1 1215.81   677.8 1217.76   706.9 1228.81   726.2 1230.85
   745.6 1237.05   755.3 1241.09   774.7 1252.42   784.4 1256.15   910.4    1280
#Mann= 3 , 0 , 0
       0      .1       0   470.6    .045       0   485.6      .1       0
Bank Sta=470.6,485.6
XS Rating Curve= 0 ,0
Exp/Cntr=0.3,0.1