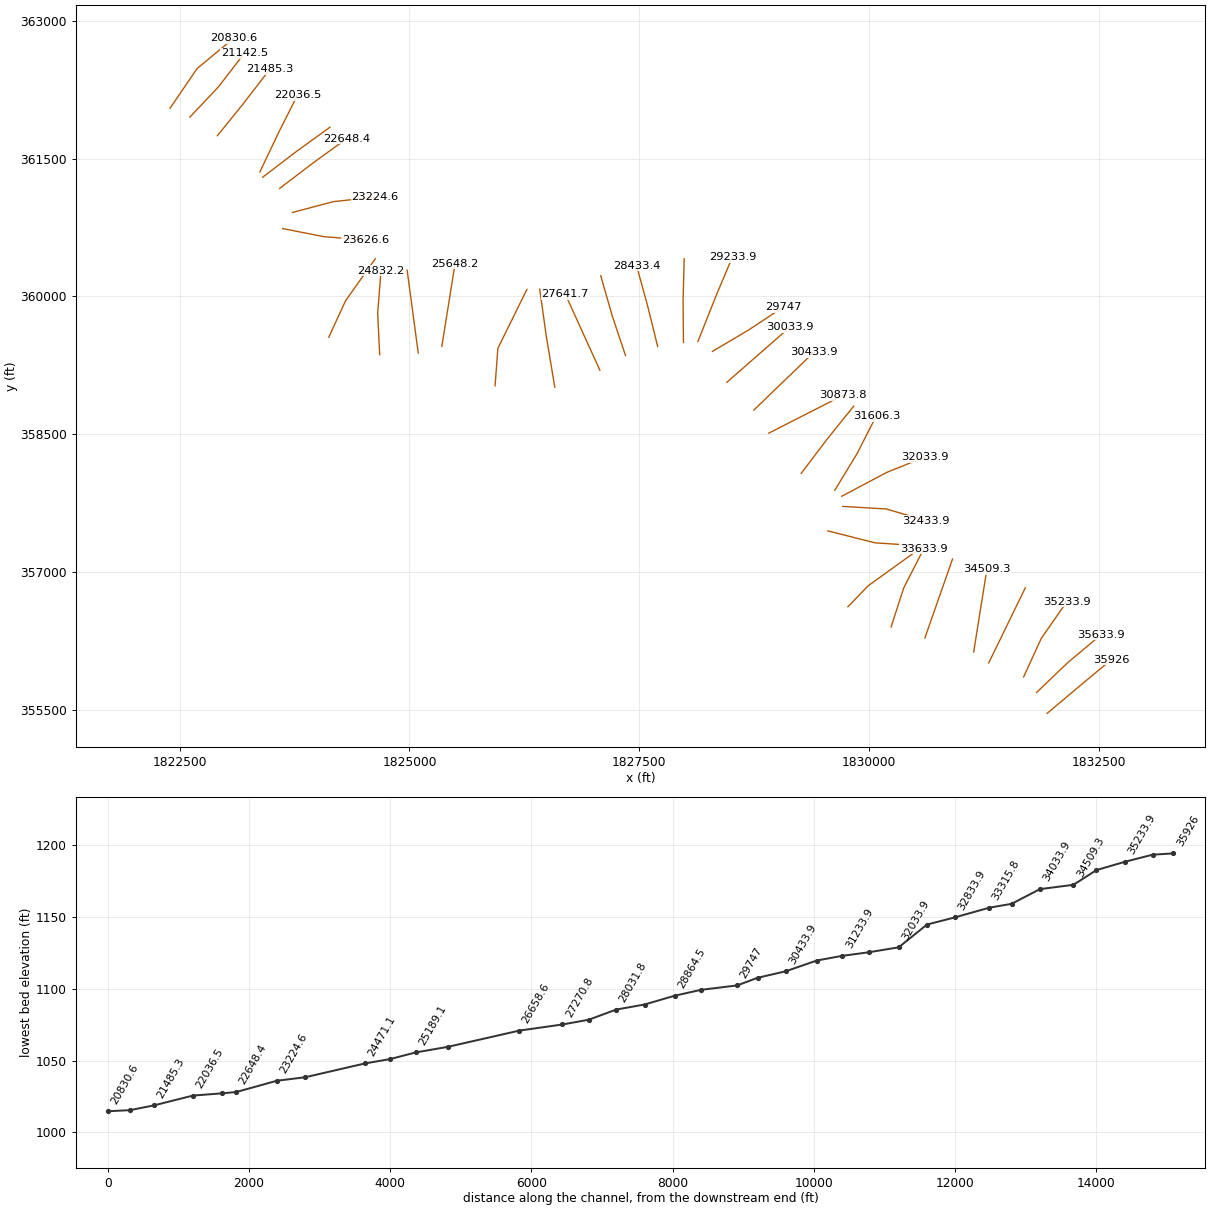
HEC-RAS study WhtdyCrk.prj: WhtdyCrk

--- WhtdyCrk.g01 (geometry) --- (continued)

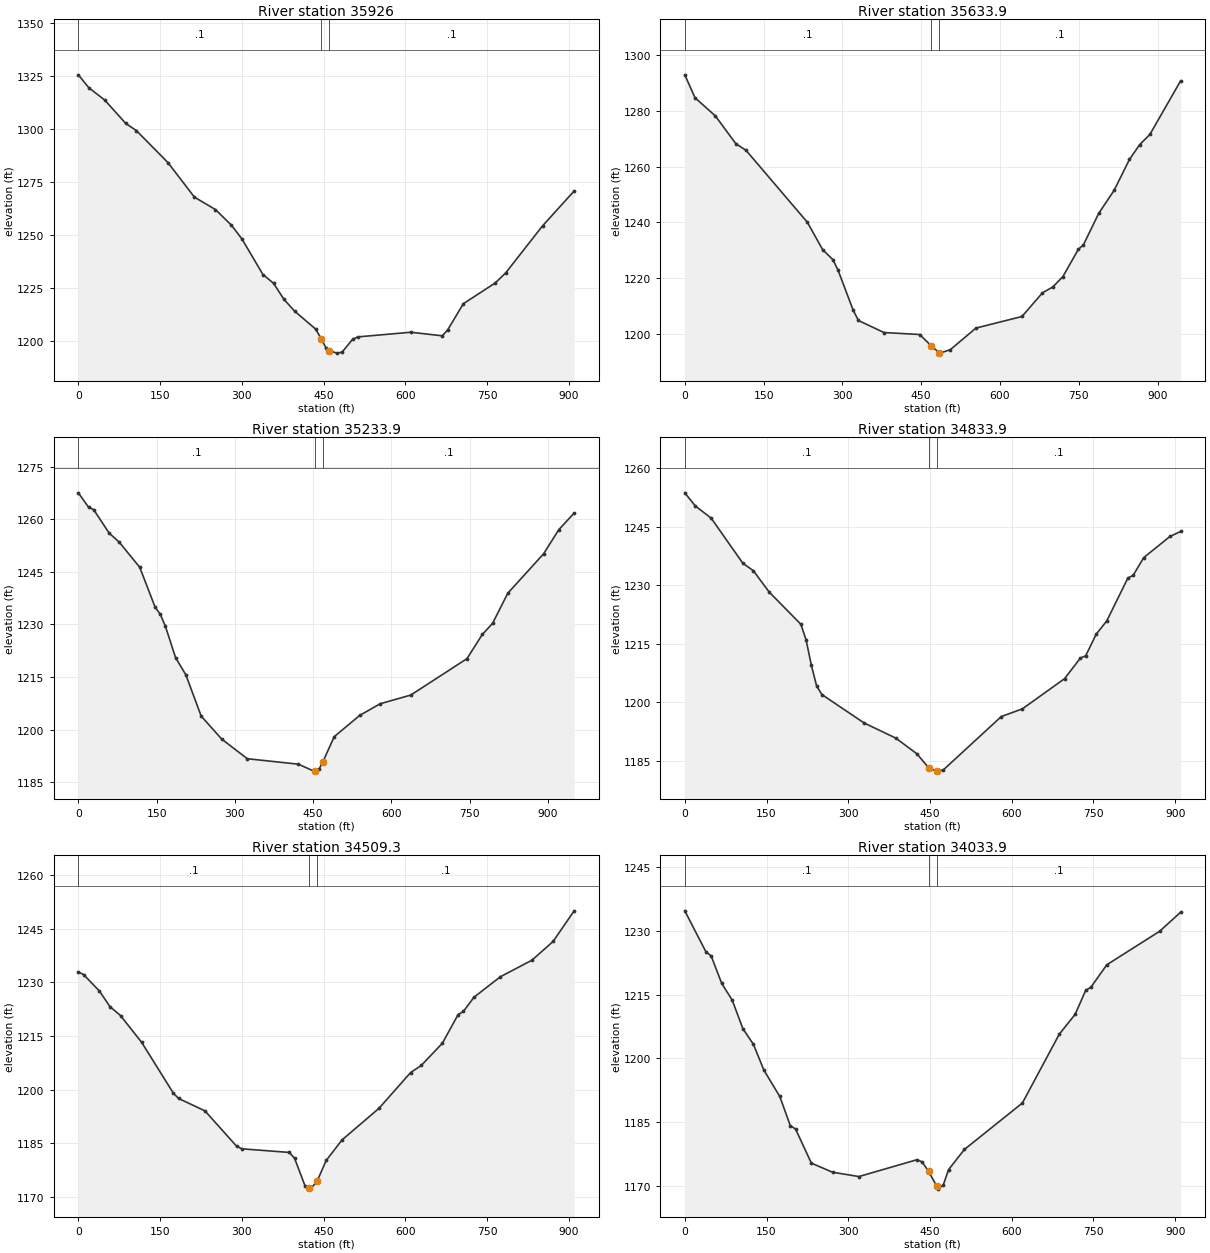
Type RM Length L Ch R = 1 ,35926   ,290.211,292.103,292.37
XS GIS Cut Line= 3
     1831938.182      355459.396     1832286.216      355752.477
     1832635.943      356043.551
#Sta/Elev= 30
       0  1325.7    19.4 1319.56    48.4 1313.78    87.1 1302.69   106.5 1299.33
   164.6 1284.15     213 1267.86   251.7 1261.96   280.7 1254.65   300.1 1248.14
   338.8 1231.25   358.2 1227.12   377.6 1219.43   396.9 1213.93   435.6 1205.42
   445.6 1200.96     455  1196.3   460.6 1195.27   474.4 1194.06     484  1194.5
   503.4 1200.62   513.1 1201.74   609.9 1203.94     668 1202.26   677.7    1205
   706.7 1217.44   764.8 1227.19   784.2 1231.96   851.9 1254.23     910 1270.76
#Mann= 3 , 0 , 0
       0      .1       0   445.6    .045       0   460.6      .1       0
Bank Sta=445.6,460.6
XS Rating Curve= 0 ,0
Exp/Cntr=0.3,0.1

Type RM Length L Ch R = 1 ,35633.9 ,391.879,400,405.636
XS GIS Cut Line= 3
     1831823.347      355687.172     1832167.417      356016.479
     1832526.176      356316.223
#Sta/Elev= 30
       0 1292.87    19.4 1284.68    58.3 1278.12    97.2 1268.19   116.6 1265.82
   233.3 1240.06   262.4 1230.26   281.9 1226.67   291.6 1222.96   320.7 1208.48
   330.5 1204.88   379.1 1200.57   447.1 1199.86   468.8 1195.86   483.8 1193.41
     486 1193.19   505.5 1194.45   554.2 1202.16   641.8 1206.31   680.8 1214.79
   700.3 1216.86   719.8 1220.63     749 1230.35   758.7 1231.95   787.9 1243.25
   817.1 1251.45   846.4 1262.57   865.8 1267.85   885.3 1271.52   943.8 1290.72
#Mann= 3 , 0 , 0
       0      .1       0   468.8    .045       0   483.8      .1       0
Bank Sta=468.8,483.8
XS Rating Curve= 0 ,0
Exp/Cntr=0.3,0.1

Type RM Length L Ch R = 1 ,35233.9 ,400.511,400,403.719
XS GIS Cut Line= 3
     1831682.247      355856.186     1831874.402      356275.432
     1832153.405      356677.345
#Sta/Elev= 30
       0 1267.54    19.6 1263.44    29.4 1262.75    58.9 1256.09    78.5 1253.46
   117.7 1246.31   147.2 1234.93     157 1232.93   166.8 1229.53   186.4 1220.55
   206.1 1215.65   235.5 1203.87   274.7 1197.35   323.8 1191.73   421.9 1190.17
   451.4 1188.19   453.7 1188.31   461.2 1188.71   468.7 1190.83   490.5 1198.02
   539.5 1204.09   578.6  1207.4   637.3 1209.88     745 1220.27   774.3 1227.15
   793.9  1230.3   823.2 1238.91   891.7 1250.14   921.1 1257.06   950.4 1261.76
#Mann= 3 , 0 , 0
       0      .1       0   453.7    .045       0   468.7      .1       0
Bank Sta=453.7,468.7
XS Rating Curve= 0 ,0
Exp/Cntr=0.3,0.1

Type RM Length L Ch R = 1 ,34833.9 ,317.814,324.651,331.488
XS GIS Cut Line= 3
     1831302.271       356008.24     1831501.548       356417.28
     1831700.824       356826.32
#Sta/Elev= 30
       0 1253.62    19.4 1250.25    48.4 1247.14   106.5 1235.61   125.9 1233.69
   154.9 1228.23     213    1220   222.7 1215.94   232.3 1209.49     242 1204.17
   251.7 1202.01   329.1 1194.74   387.2 1190.87     426 1186.85   447.5 1183.28
   462.5 1182.43   464.7 1182.42   474.4 1182.72   580.9 1196.39   619.6 1198.35
     697 1206.08   726.1 1211.35   735.7 1211.92   755.1 1217.46   774.5 1220.87
   813.2 1231.83   822.9  1232.5   842.2 1237.04   890.6 1242.47     910 1243.73
#Mann= 3 , 0 , 0
       0      .1       0   447.5    .045       0   462.5      .1       0
Bank Sta=447.5,462.5
XS Rating Curve= 0 ,0
Exp/Cntr=0.3,0.1

Type RM Length L Ch R = 1 ,34509.3 ,479.559,475.349,471.139
XS GIS Cut Line= 3
     1831138.991      356127.648     1831210.711       356576.96
     1831282.431      357026.272
#Sta/Elev= 30
       0 1232.88     9.7 1232.15    38.7 1227.54    58.1 1223.19    77.4  1220.7
   116.2 1213.22   174.3 1199.05   183.9 1197.55   232.3 1194.09   290.4 1184.22
   300.1 1183.48   387.2 1182.47   396.9 1180.82   416.3 1173.04   423.4 1172.44
     426 1172.22   438.4 1174.51     455 1180.25     484 1185.97   551.8 1194.79
   609.9 1204.79   629.3 1206.75     668 1212.94     697 1220.96   706.7 1221.85
   726.1 1225.81   774.5 1231.53   832.6 1236.17   871.3 1241.39     910 1249.95
#Mann= 3 , 0 , 0
       0      .1       0   423.4    .045       0   438.4      .1       0
Bank Sta=423.4,438.4
XS Rating Curve= 0 ,0
Exp/Cntr=0.3,0.1

Type RM Length L Ch R = 1 ,34033.9 ,399.485,400,396.901
XS GIS Cut Line= 3
     1830608.238      356280.982     1830758.548      356710.437
     1830908.858      357139.893
#Sta/Elev= 30
       0 1234.72    38.7 1225.09    48.4  1224.1    67.8 1217.63    87.1 1213.68
   106.5 1207.01   125.9 1203.31   145.2 1197.21   174.3 1191.04   193.6 1184.17
   203.3 1183.36   232.3 1175.34   271.1  1173.2   319.5 1172.18     426 1176.14
   435.6 1175.64   447.5 1173.37   462.5  1169.9   464.7 1169.22   474.4 1170.19
     484 1173.79   513.1 1178.55   619.6 1189.49   687.3 1205.69   716.4 1210.35
   735.7 1215.98   745.4 1216.75   774.5 1222.02   871.3 1229.89     910 1234.39
#Mann= 3 , 0 , 0
       0      .1       0   447.5    .045       0   462.5      .1       0
Bank Sta=447.5,462.5
XS Rating Curve= 0 ,0
Exp/Cntr=0.3,0.1

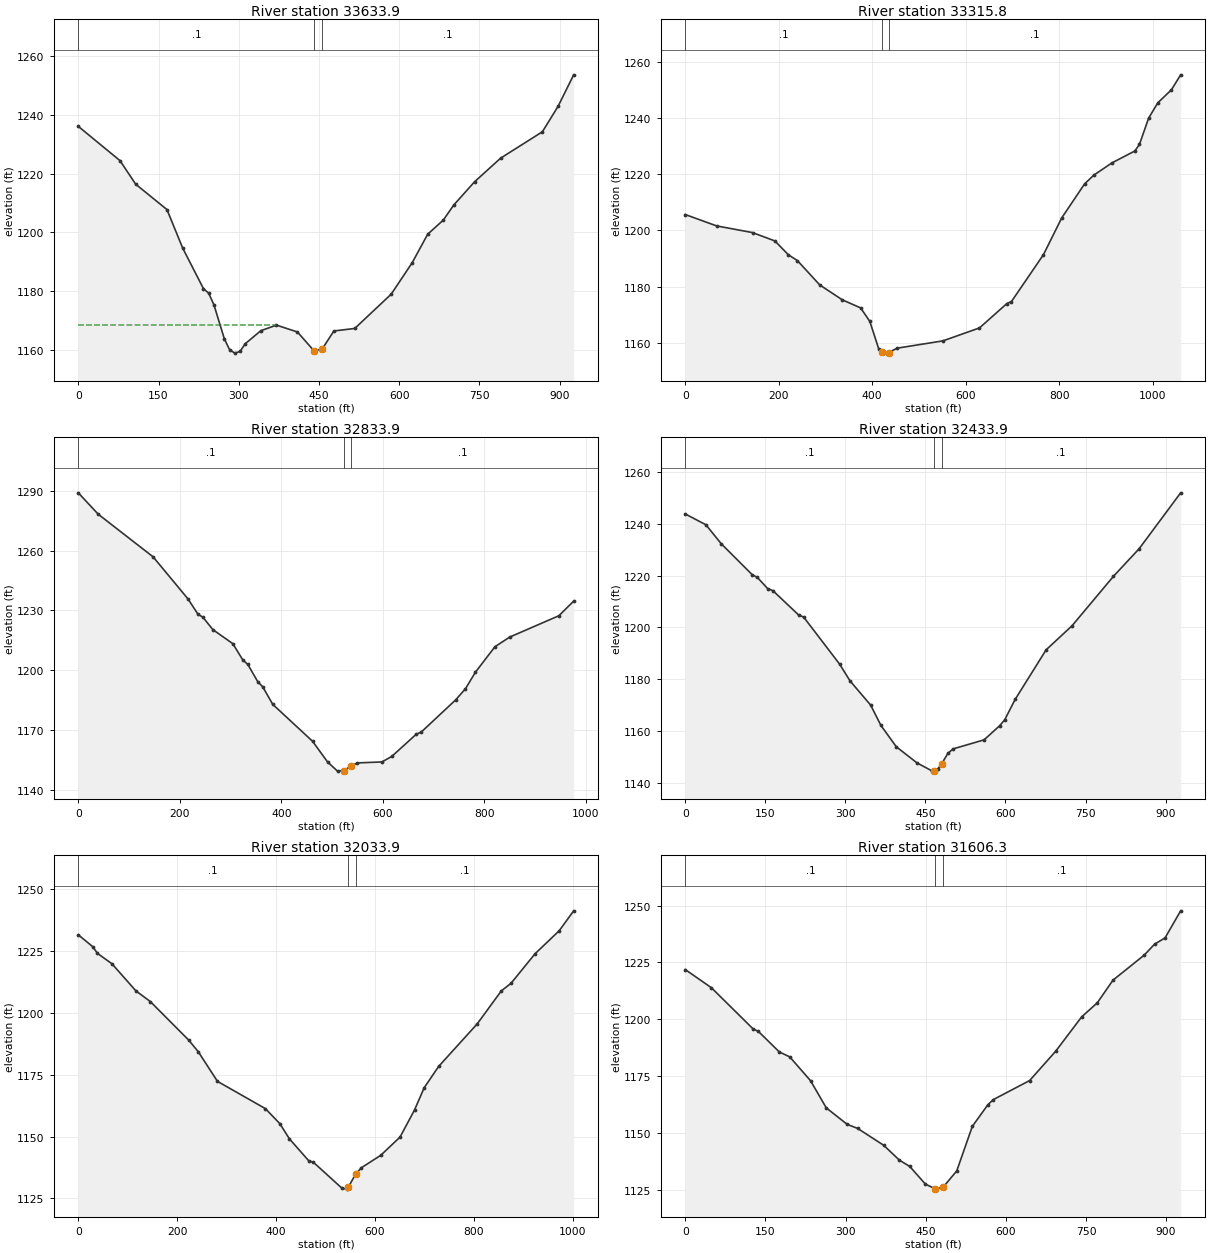
Type RM Length L Ch R = 1 ,33633.9 ,332.547,318.135,307.337
XS GIS Cut Line= 3
     1830240.255      356400.099     1830378.499      356826.939
     1830596.309      357252.034
#Sta/Elev= 30
       0 1236.04      78 1224.39   107.3 1216.39   165.8 1207.77   195.1 1194.72
   234.1 1180.88   243.8 1179.37   253.6 1175.41   273.1 1163.86   282.9 1160.15
   292.6    1159   302.4 1159.56   312.1 1162.18   341.4 1166.63   370.6 1168.51
   409.7 1166.19   441.2  1159.7   456.2 1160.43   477.9 1166.53   516.9 1167.38
   585.1 1179.03   624.1 1189.64   653.4 1199.41   682.6 1204.21   702.1 1209.32
   741.1 1217.23   789.8 1225.25   867.8  1234.2   897.1 1242.82   926.3 1253.55
#Mann= 3 , 0 , 0
       0      .1       0   441.2    .045       0   456.2      .1       0
#XS Ineff= 2 , 0
          370.24 1168.58
Permanent Ineff=
       F       F
Bank Sta=441.2,456.2
XS Rating Curve= 0 ,0
Exp/Cntr=0.3,0.1

Type RM Length L Ch R = 1 ,33315.8 ,502.919,481.865,465.515
XS GIS Cut Line= 3
     1829770.975      356620.255     1829990.555      356848.199
     1830593.793      357282.751
#Sta/Elev= 30
       0 1205.61    67.1 1201.56   143.9 1199.19   191.8 1196.21   220.6 1191.28
   239.8 1189.24   287.7 1180.56   336.1 1175.25   375.2 1172.38   394.8 1167.61
   414.3 1157.62     420 1156.85   424.1 1156.29     435 1156.48   453.5 1158.06
   551.3 1160.65   629.5 1165.26   688.2 1173.94     698 1174.66   766.5 1191.36
   805.6 1204.44   854.5 1216.53   874.1 1219.62   913.2 1224.01   962.1 1228.24
   971.9 1230.59   991.5 1239.93  1011.1 1245.36  1040.4 1250.03    1060 1255.33
#Mann= 3 , 0 , 0
       0      .1       0     420    .045       0     435      .1       0
Bank Sta=420,435
XS Rating Curve= 0 ,0
Exp/Cntr=0.3,0.1

Type RM Length L Ch R = 1 ,32833.9 ,395.242,400,394.037
XS GIS Cut Line= 3
     1829551.773      357446.186     1830066.154      357316.089
     1830510.882      357286.982
#Sta/Elev= 30
       0 1288.87    39.3 1278.16   147.4 1256.85   216.2 1235.78   235.8 1228.15
   245.6 1226.63   265.3  1220.4   304.6 1213.39   324.2 1205.25   334.1    1203
   353.7 1194.37   363.5  1191.8   383.2 1183.04   461.8 1164.54   491.3 1154.21
   510.9 1149.63   523.1  1149.9   538.1 1152.26     550 1153.74   598.4 1154.23
   617.8 1156.98   666.2 1168.13   675.9 1169.17   743.7 1185.27   763.1 1190.86
   782.5 1199.05   821.2 1211.89   850.3  1216.7   947.2 1227.38   976.3 1234.68
#Mann= 3 , 0 , 0
       0      .1       0   523.1    .045       0   538.1      .1       0
Bank Sta=523.1,538.1
XS Rating Curve= 0 ,0
Exp/Cntr=0.3,0.1

Type RM Length L Ch R = 1 ,32433.9 ,387.393,400,415.75
XS GIS Cut Line= 3
     1829714.054      357712.336     1830185.961      357685.272
     1830623.166      357557.154
#Sta/Elev= 30
       0 1243.75    38.6  1239.6    67.5 1232.24   125.4 1220.34   135.1 1219.28
   154.3 1214.98     164 1214.21   212.2 1204.83   221.9 1203.97   289.4 1185.78
   308.7 1179.37   347.3 1170.06   366.6  1162.2   395.5 1153.95   434.1 1147.77
     463 1144.57   465.2 1144.74   472.7 1145.31   480.2 1147.32   492.1 1151.42
   501.8 1153.15   559.9 1156.63     589 1162.05   598.7 1164.41   618.1 1172.22
   676.2 1191.36   724.7 1200.62   802.3 1219.69   850.7 1230.39   928.3 1251.91
#Mann= 3 , 0 , 0
       0      .1       0   465.2    .045       0   480.2      .1       0
Bank Sta=465.2,480.2
XS Rating Curve= 0 ,0
Exp/Cntr=0.3,0.1

Type RM Length L Ch R = 1 ,32033.9 ,411.483,427.624,445.502
XS GIS Cut Line= 3
     1829703.047      357823.212     1830191.773      358082.415
     1830607.958      358249.974
#Sta/Elev= 30
       0 1231.48    29.1  1226.7    38.8 1223.97    67.9 1219.82   116.5 1208.83
   145.6 1204.54   223.2 1188.97   242.6 1184.27   281.5 1172.28   378.5 1161.26
   407.6  1155.2     427 1149.06   465.9 1140.25   475.6 1139.58   533.8 1129.02
   543.5 1128.75   545.7 1129.41   560.7 1134.73   572.7 1137.41   611.7 1142.41
   650.7 1149.77     680 1160.71   699.5 1169.69   728.8 1178.31   806.8  1195.5
   855.6 1208.83   875.1 1211.87   923.8 1223.83   972.6 1233.11  1001.9 1241.17
#Mann= 3 , 0 , 0
       0      .1       0   545.7    .045       0   560.7      .1       0
Bank Sta=545.7,560.7
XS Rating Curve= 0 ,0
Exp/Cntr=0.3,0.1

Type RM Length L Ch R = 1 ,31606.3 ,376.001,372.376,367.635
XS GIS Cut Line= 3
     1829628.058       357888.34     1829866.298      358281.038
     1830079.557      358697.505
#Sta/Elev= 30
       0 1221.88    48.9 1213.89     127 1195.75   136.8 1194.68   175.9 1185.66
   195.5 1183.47   234.5 1172.97   263.9 1161.03     303 1153.78   322.5 1152.01
   371.4 1144.57   400.7 1138.03   420.2 1135.25   449.5 1127.48   468.3 1125.36
   469.1 1125.28   483.3 1126.33   508.1 1133.29   537.3 1152.91   566.5 1162.44
   576.3 1164.64   644.5 1173.05   693.3 1185.96     742  1201.1   771.2 1207.25
   800.5 1217.21     859 1228.24   878.5 1233.08     898 1235.82   927.2 1247.73
#Mann= 3 , 0 , 0
       0      .1       0   468.3    .045       0   483.3      .1       0
Bank Sta=468.3,483.3
XS Rating Curve= 0 ,0
Exp/Cntr=0.3,0.1

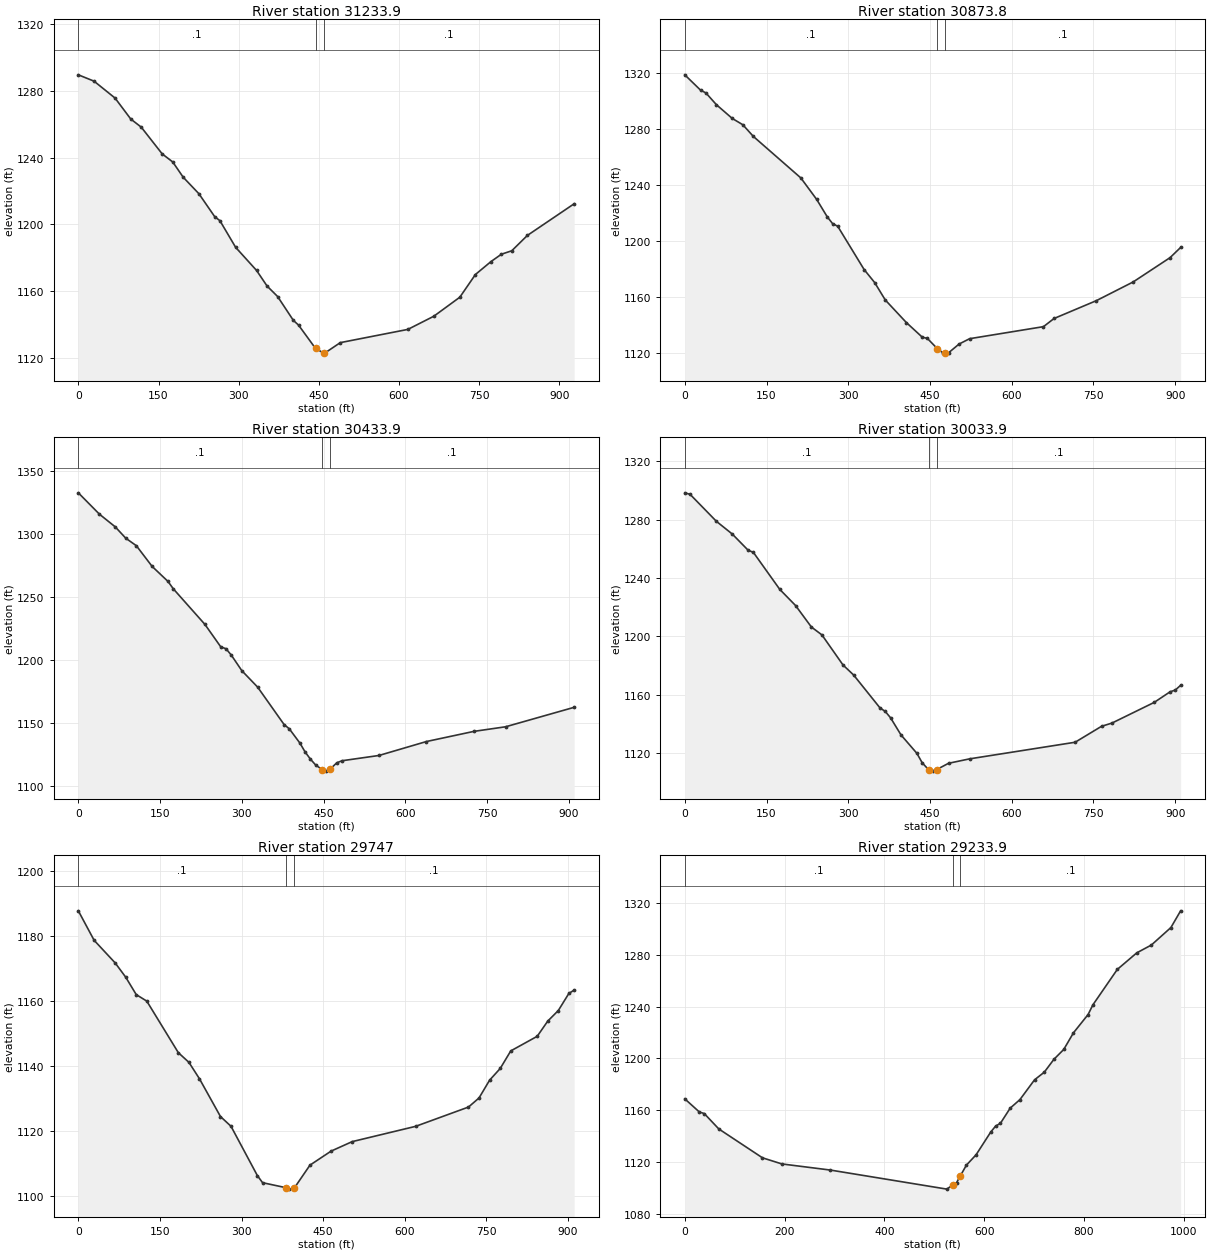
Type RM Length L Ch R = 1 ,31233.9 ,370.481,360.186,350.568
XS GIS Cut Line= 3
     1829263.043      358073.222     1829535.117      358433.197
     1829833.645      358804.432
#Sta/Elev= 30
       0 1289.61    29.4 1285.81    68.7 1275.68    98.1 1263.12   117.7 1258.25
   156.9 1242.22   176.6  1237.4   196.2 1228.24   225.6 1218.34     255 1204.67
   264.9 1202.18   294.3 1186.23   333.5 1172.36   353.1 1163.03   372.8 1156.76
   402.2 1142.49     412 1139.62   443.7 1125.66   458.7 1122.93   460.9 1122.83
   490.1 1129.12   616.5 1137.05   665.1 1144.95   713.7 1156.34   742.9 1169.95
   772.1 1177.72   791.5  1182.1   810.9 1184.17   840.1 1193.37   927.6 1212.34
#Mann= 3 , 0 , 0
       0      .1       0   443.7    .045       0   458.7      .1       0
Bank Sta=443.7,458.7
XS Rating Curve= 0 ,0
Exp/Cntr=0.3,0.1

Type RM Length L Ch R = 1 ,30873.8 ,433.118,439.814,446.51
XS GIS Cut Line= 3
     1828909.481      358510.185       1829314.8      358716.925
     1829720.119      358923.665
#Sta/Elev= 30
       0 1318.86      29 1307.86    38.7 1305.92    58.1 1297.44    87.1 1287.63
   106.5 1283.11   125.9 1274.72     213 1245.02     242 1229.67   261.4 1217.19
   271.1 1212.39   280.7 1210.39   329.1 1179.44   348.5  1170.1   367.9 1157.66
   406.6 1141.49   435.6 1131.08   445.3 1130.07   463.4 1122.82   474.4 1119.58
   478.4 1119.67     484 1119.79   503.4 1126.09   522.8 1129.92   658.3 1138.54
   677.7 1144.38   755.1 1157.11   822.9 1170.55   890.6 1187.95     910 1195.25
#Mann= 3 , 0 , 0
       0      .1       0   463.4    .045       0   478.4      .1       0
Bank Sta=463.4,478.4
XS Rating Curve= 0 ,0
Exp/Cntr=0.3,0.1

Type RM Length L Ch R = 1 ,30433.9 ,401.075,400,398.925
XS GIS Cut Line= 3
     1828747.459      358761.801     1829074.919      359077.704
      1829402.38      359393.607
#Sta/Elev= 30
       0 1332.65    38.7 1315.73    67.8 1305.66    87.1 1296.67   106.5 1290.74
   135.5 1274.31   164.6 1262.42   174.3 1256.58   232.3  1228.4   261.4 1210.59
   271.1 1209.07   280.7 1204.08   300.1 1191.69   329.1 1178.67   377.6 1149.04
   387.2 1145.63   406.6 1134.37   416.3 1127.23     426 1121.58   435.6 1116.94
   447.5 1113.32     455  1112.1   462.5 1113.85   474.4 1118.72     484 1120.33
   551.8 1124.51   638.9 1135.56   726.1 1143.61   784.1 1147.24     910 1162.67
#Mann= 3 , 0 , 0
       0      .1       0   447.5    .045       0   462.5      .1       0
Bank Sta=447.5,462.5
XS Rating Curve= 0 ,0
Exp/Cntr=0.3,0.1

Type RM Length L Ch R = 1 ,30033.9 ,291.08,286.911,282.742
XS GIS Cut Line= 3
      1828453.97       359064.37      1828796.13       359364.29
      1829138.29      359664.209
#Sta/Elev= 30
       0 1298.32     9.7 1297.29    58.1 1278.75    87.1 1270.08   116.2 1258.99
   125.9 1257.48   174.3 1232.14   203.3 1221.06   232.3 1206.35   251.7 1200.92
   290.4  1180.3   309.8 1173.46   358.2 1150.91   367.9 1148.47   377.6 1144.13
   396.9 1132.32     426 1119.74   435.6 1113.33   447.5 1108.51     455 1107.55
   462.5 1108.66     484 1112.92   522.8 1115.97   716.4 1127.35   764.8 1138.27
   784.1 1140.51   861.6 1154.68   890.6 1161.91   900.3 1163.15     910 1166.37
#Mann= 3 , 0 , 0
       0      .1       0   447.5    .045       0   462.5      .1       0
Bank Sta=447.5,462.5
XS Rating Curve= 0 ,0
Exp/Cntr=0.3,0.1

Type RM Length L Ch R = 1 ,29747   ,498.052,513.089,527.684
XS GIS Cut Line= 3
     1828296.114      359399.956     1828687.393      359631.666
     1829068.165      359883.483
#Sta/Elev= 30
       0 1187.85      29 1178.79    67.7 1171.83    87.1 1167.44   106.4 1162.09
   125.8 1160.08   183.8 1144.22   203.2 1141.26   222.5 1136.23   261.2 1124.59
   280.6 1121.58     329 1106.43   338.6 1104.24   381.6  1102.7     387 1102.26
   396.6 1102.52   425.7 1109.64   464.5 1113.95   503.3 1116.87   619.9 1121.57
     717  1127.5   736.4  1130.3   755.8 1135.77   775.3 1139.36   794.7 1144.77
   843.3 1149.26   862.7 1153.94   882.1 1157.19   901.5 1162.45   911.2 1163.47
#Mann= 3 , 0 , 0
       0      .1       0   381.6    .045       0   396.6      .1       0
Bank Sta=381.6,396.6
XS Rating Curve= 0 ,0
Exp/Cntr=0.3,0.1

Type RM Length L Ch R = 1 ,29233.9 ,361.479,369.463,377.888
XS GIS Cut Line= 3
     1828138.348      359508.077     1828339.557      360014.207
     1828513.509      360427.933
#Sta/Elev= 30
       0 1168.83    29.2 1158.68    38.9 1157.52    68.1 1145.63   155.6 1123.35
   194.5 1118.62   291.8 1113.89   525.2 1099.19   537.2 1102.56   544.7 1104.26
   552.2 1109.48   564.2 1117.67   583.7  1125.7     613 1143.22   622.7 1147.78
   632.5    1150     652 1161.67   671.5 1168.24   700.8 1183.51   720.3  1189.4
   739.8 1199.41   759.3 1206.93   778.8 1219.78   808.1 1233.88   817.8 1241.39
   866.6 1268.66   905.7 1281.47   934.9 1287.49     974 1300.96   993.5 1313.87
#Mann= 3 , 0 , 0
       0      .1       0   537.2    .045       0   552.2      .1       0
Bank Sta=537.2,552.2
XS Rating Curve= 0 ,0
Exp/Cntr=0.3,0.1

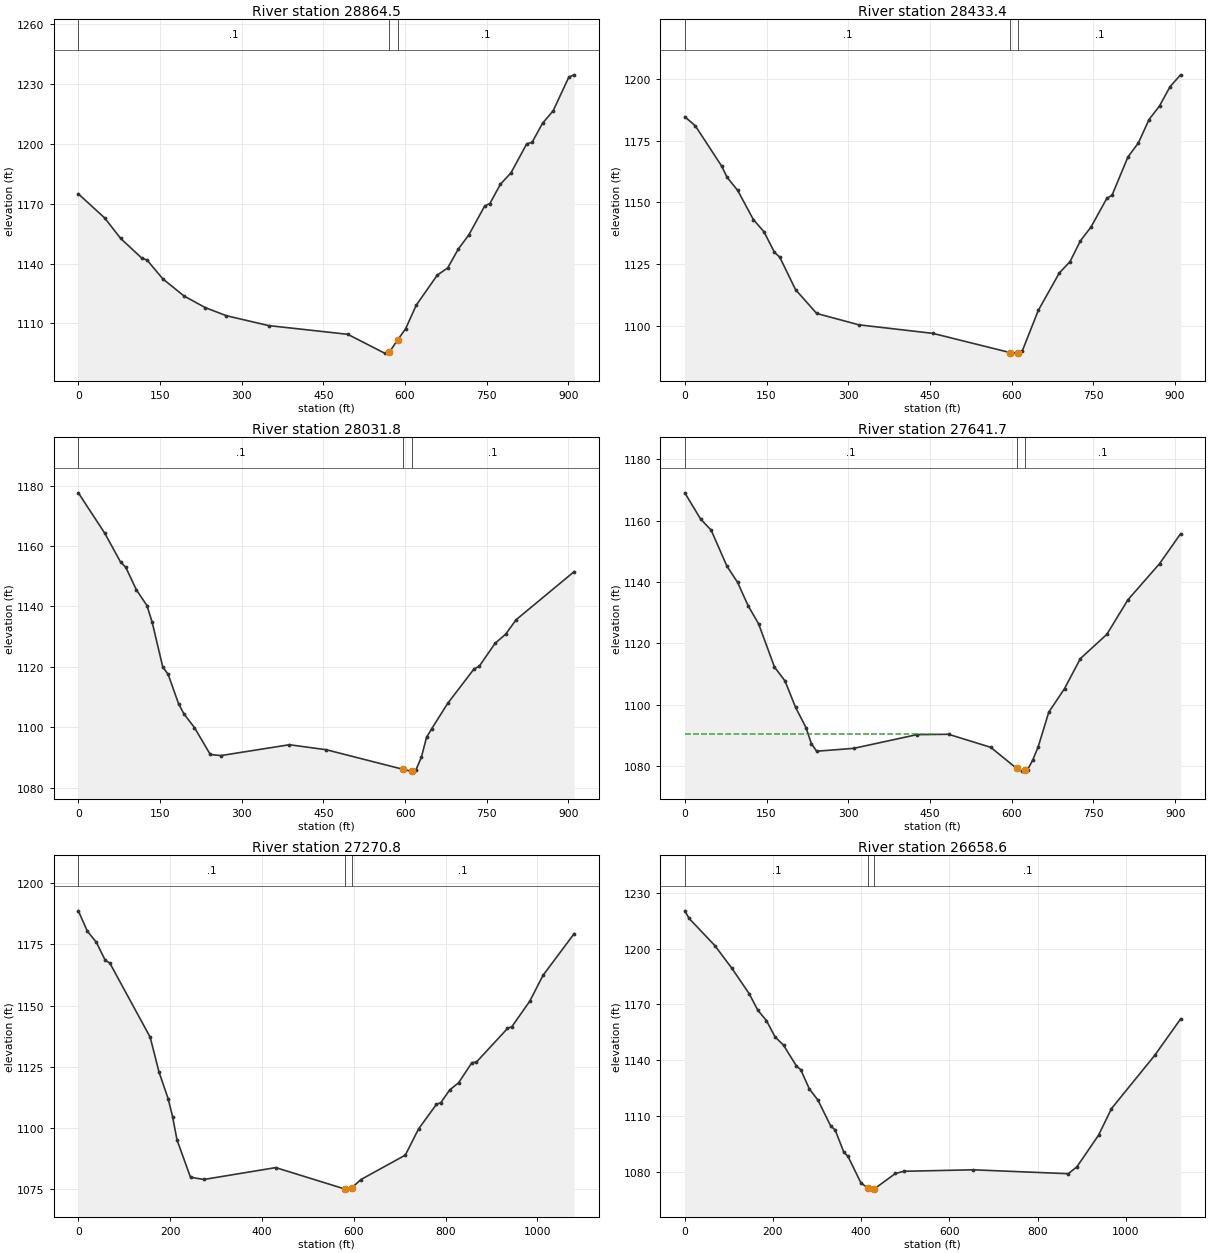
Type RM Length L Ch R = 1 ,28864.5 ,424.429,431.078,437.727
XS GIS Cut Line= 3
     1827981.177      359497.277     1827976.944       359953.39
     1827989.219      360407.888
#Sta/Elev= 30
       0 1174.91    48.5 1162.82    77.6 1152.62   116.5 1142.74   126.2 1141.76
   155.3 1132.31   194.1 1123.78   232.9 1117.99   271.7 1113.91   349.4 1108.95
   494.8 1104.58   562.5 1095.15   571.3 1095.57   586.3  1101.7   601.2 1107.34
   620.6  1119.1   659.3 1134.19   678.6 1137.85     698 1147.28   717.3 1154.35
   746.3 1168.76     756 1170.07   775.4 1179.76   794.7 1185.41   823.7 1199.97
   833.4 1200.65   852.8 1210.28   872.1 1216.46   901.1 1233.41   910.8 1234.51
#Mann= 3 , 0 , 0
       0      .1       0   571.3    .045       0   586.3      .1       0
Bank Sta=571.3,586.3
XS Rating Curve= 0 ,0
Exp/Cntr=0.3,0.1

Type RM Length L Ch R = 1 ,28433.4 ,401.352,401.593,401.834
XS GIS Cut Line= 3
     1827700.903      359453.475     1827591.351      359895.261
      1827471.05      360334.039
#Sta/Elev= 30
       0 1184.75    19.4 1181.03    67.8 1164.69    77.5 1160.24    96.8 1154.98
   125.9 1143.08   145.3 1138.14   164.6 1129.83   174.3 1127.85   203.4 1114.65
   242.1 1105.05   319.6 1100.44   455.2 1096.99   596.5 1089.23   600.4 1088.98
   611.5 1089.21   619.7 1090.01   648.8 1106.26   687.5 1121.49   706.9 1125.97
   726.2 1134.49   745.6 1140.06   774.6 1151.67   784.3 1152.98   813.3 1168.41
   832.7 1174.18   852.1 1183.61   871.4 1189.13   890.8 1196.96   910.1 1201.71
#Mann= 3 , 0 , 0
       0      .1       0   596.5    .045       0   611.5      .1       0
Bank Sta=596.5,611.5
XS Rating Curve= 0 ,0
Exp/Cntr=0.3,0.1

Type RM Length L Ch R = 1 ,28031.8 ,386.798,390.154,393.509
XS GIS Cut Line= 3
      1827350.97      359354.569     1827206.405      359786.573
     1827081.434      360223.973
#Sta/Elev= 30
       0  1177.6    48.5 1164.24    77.5  1154.7    87.2 1152.92   106.6 1145.48
     126 1140.28   135.7  1134.7   155.1 1119.89   164.8 1117.56   184.2 1107.72
   193.9 1104.42   213.2 1099.89   242.3 1090.97   261.7 1090.61   387.7  1094.2
   455.6 1092.53   596.9 1086.03   610.4 1085.46   611.9 1085.53   620.1 1085.95
   629.8 1089.99   639.4 1096.64   649.1 1099.55   678.2 1107.88   726.6 1119.29
   736.2 1120.17   765.3 1127.78   784.6 1130.78     804  1135.6   910.5 1151.51
#Mann= 3 , 0 , 0
       0      .1       0   596.9    .045       0   611.9      .1       0
#XS Ineff= 2 , 0
          396.81 1093.95
Permanent Ineff=
       F       F
Bank Sta=596.9,611.9
XS Rating Curve= 0 ,0
Exp/Cntr=0.3,0.1

Type RM Length L Ch R = 1 ,27641.7 ,377.764,370.869,363.898
XS GIS Cut Line= 3
     1827072.046       359195.04     1826883.765      359609.257
     1826695.485      360023.473
#Sta/Elev= 30
       0 1169.06      29 1160.52    48.4 1156.89    77.4 1145.15    96.8 1139.92
   116.2 1132.28   135.5 1126.35   164.6  1112.3   183.9 1107.78   203.3 1099.16
   222.7 1092.46   232.3 1087.31     242 1084.87   309.8  1085.8     426 1090.27
     484 1090.39   561.5 1086.14   608.8  1079.3   619.6 1078.38   623.8  1078.6
   629.3  1078.9   638.9 1082.12   648.6 1086.32     668 1097.58     697  1105.3
   726.1 1115.07   774.5 1122.93   813.2 1134.19   871.3 1145.97     910 1155.74
#Mann= 3 , 0 , 0
       0      .1       0   608.8    .045       0   623.8      .1       0
#XS Ineff= 2 , 0
          465.01 1090.47
Permanent Ineff=
       F       F
Bank Sta=608.8,623.8
XS Rating Curve= 0 ,0
Exp/Cntr=0.3,0.1

Type RM Length L Ch R = 1 ,27270.8 ,620.38,612.2,599.314
XS GIS Cut Line= 3
     1826581.252      359011.048     1826488.059      359570.205
     1826417.395      360078.316
#Sta/Elev= 30
       0 1188.73    19.5 1180.47    39.1 1175.93    58.6 1168.53    68.4 1167.45
   156.4 1137.16   175.9 1122.79   195.5  1112.1   205.2 1104.74     215 1095.15
   244.3 1079.94   273.7 1079.05     430 1083.89   581.1 1075.11   586.2  1075.1
   596.1 1075.73   615.3 1078.99   712.1 1088.98   741.1 1099.69   779.8 1109.69
   789.5 1110.42   808.9 1115.63   828.2 1118.52   857.2 1126.76   866.9 1126.95
   934.7  1140.7   944.4 1141.47   983.1 1151.82  1012.1 1162.39  1079.9 1179.42
#Mann= 3 , 0 , 0
       0      .1       0   581.1    .045       0   596.1      .1       0
Bank Sta=581.1,596.1
XS Rating Curve= 0 ,0
Exp/Cntr=0.3,0.1

Type RM Length L Ch R = 1 ,26658.6 ,1007.924,1010.404,1017.658
XS GIS Cut Line= 3
     1825931.455      359025.858     1825962.064      359433.768
     1826278.133      360075.504
#Sta/Elev= 30
       0 1220.26     9.7 1216.21    68.2 1201.58   107.1  1189.3   146.1 1175.74
   165.6 1166.89     185 1161.37   204.5 1152.66     224 1148.08   253.2 1136.93
     263 1134.95   282.4 1124.66   301.9 1118.65   331.1 1104.64   340.9 1102.66
   360.4  1090.8   370.1 1088.41   399.3 1074.23   415.1 1071.37   428.7 1070.83
   430.1 1071.01   477.7 1079.25   497.2 1080.41     654 1081.21   869.6 1079.11
   889.2 1082.82   938.2 1099.76   967.6 1114.07  1065.6 1142.65  1124.4 1162.23
#Mann= 3 , 0 , 0
       0      .1       0   415.1    .045       0   430.1      .1       0
Bank Sta=415.1,430.1
XS Rating Curve= 0 ,0
Exp/Cntr=0.3,0.1

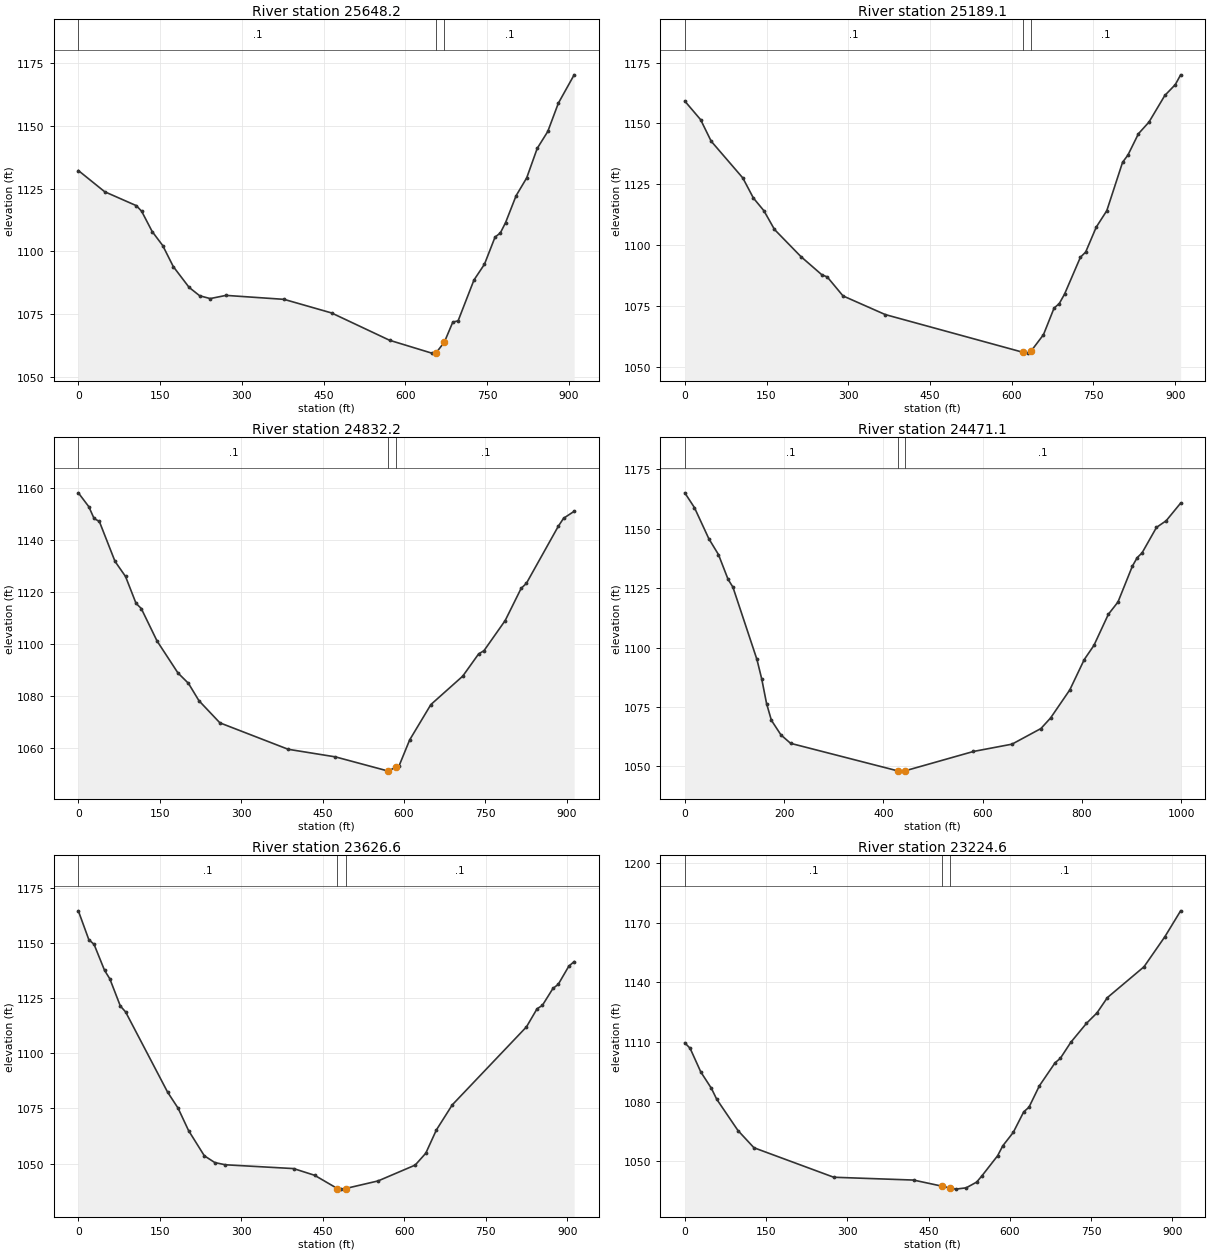
Type RM Length L Ch R = 1 ,25648.2 ,452.081,459.116,466.151
XS GIS Cut Line= 3
     1825352.066      359454.886     1825424.108      359904.146
      1825496.15      360353.407
#Sta/Elev= 30
       0  1132.2    48.4 1123.75   106.5 1118.21   116.2 1115.99   135.5 1107.93
   154.9 1102.34   174.3 1093.97   203.3 1085.71   222.7 1082.37     242 1081.25
   271.1 1082.52   377.6 1080.94   464.7 1075.54   571.2 1064.67   648.6 1059.55
   656.8 1059.72   671.8 1063.94   687.3  1071.9     697 1072.39   726.1 1088.63
   745.4 1094.92   764.8 1105.71   774.5 1107.34   784.1 1111.46   803.5 1122.19
   822.9 1129.26   842.2    1141   861.6 1147.73     881 1158.98     910 1170.26
#Mann= 3 , 0 , 0
       0      .1       0   656.8    .045       0   671.8      .1       0
Bank Sta=656.8,671.8
XS Rating Curve= 0 ,0
Exp/Cntr=0.3,0.1

Type RM Length L Ch R = 1 ,25189.1 ,361.659,356.877,352.096
XS GIS Cut Line= 3
     1825095.547      359382.967     1825035.093      359833.933
      1824974.64      360284.899
#Sta/Elev= 30
       0 1159.17      29 1151.54    48.4 1142.69   106.5 1127.58   125.9 1119.34
   145.2 1114.12   164.6 1106.43     213 1095.31   251.7 1087.78   261.4 1086.94
   290.4 1079.13   367.9 1071.47   620.9 1055.96   629.3 1055.63   635.9 1056.58
   658.3 1063.22   677.7 1074.12   687.3    1076     697 1079.89   726.1 1095.03
   735.7 1097.14   755.1 1107.37   774.5 1114.15   803.5 1134.04   813.2 1136.96
   832.6 1145.76   851.9 1150.54     881 1161.47   900.3 1165.95     910 1169.95
#Mann= 3 , 0 , 0
       0      .1       0   620.9    .045       0   635.9      .1       0
Bank Sta=620.9,635.9
XS Rating Curve= 0 ,0
Exp/Cntr=0.3,0.1

Type RM Length L Ch R = 1 ,24832.2 ,369.104,361.07,348.382
XS GIS Cut Line= 3
     1824675.988      359365.281     1824654.184      359818.959
     1824690.696      360277.032
#Sta/Elev= 30
       0 1158.15    19.3 1152.82      29 1148.28    38.7 1147.15    67.6 1131.78
      87 1125.96   106.3 1115.65     116 1113.63     145 1101.17   183.6 1088.84
   202.9 1084.86   222.3 1078.17   260.9 1069.65   386.6 1059.49   473.8 1056.56
   571.3 1051.09   571.5 1051.08   586.3 1052.83   591.1 1053.14   610.6  1063.1
   649.7  1076.7   708.4 1087.63   737.7 1096.19   747.5 1097.41   786.6 1109.02
     816 1121.39   825.7 1123.34   884.4 1145.26   894.2 1148.36   913.7 1151.04
#Mann= 3 , 0 , 0
       0      .1       0   571.3    .045       0   586.3      .1       0
Bank Sta=571.3,586.3
XS Rating Curve= 0 ,0
Exp/Cntr=0.3,0.1

Type RM Length L Ch R = 1 ,24471.1 ,872.358,844.55,821.234
XS GIS Cut Line= 3
     1824122.438      359554.542     1824304.268       359950.82
     1824629.248      360410.128
#Sta/Elev= 30
       0 1165.09    19.4 1158.88    48.4 1145.79    67.8 1139.12    87.2 1128.67
    96.9 1125.42   145.3 1094.97     155 1086.72   164.7 1076.42   174.4 1069.39
   193.8 1063.18   213.2 1059.67   428.7  1048.1     436 1047.98   443.7 1048.11
   581.5 1056.26   659.1 1059.33   717.3  1065.9   736.7 1070.33   775.5 1082.18
   804.6 1094.94     824 1100.86   853.1 1113.96   872.5 1119.14   901.6 1134.28
   911.3 1137.83     921 1139.81   950.1 1150.55   969.6 1153.34   998.7 1160.76
#Mann= 3 , 0 , 0
       0      .1       0   428.7    .045       0   443.7      .1       0
Bank Sta=428.7,443.7
XS Rating Curve= 0 ,0
Exp/Cntr=0.3,0.1

Type RM Length L Ch R = 1 ,23626.6 ,395.524,401.927,407.228
XS GIS Cut Line= 3
     1823620.141      360737.626     1824066.006      360650.046
     1824522.946      360612.492
#Sta/Elev= 30
       0 1164.56    19.3  1151.5      29 1149.34    48.3 1137.56      58 1133.73
    77.3 1121.43      87 1118.74   164.4 1082.35   183.7 1075.08     203 1064.93
     232 1053.51   251.4 1050.43   270.7 1049.44   396.4 1047.71   435.1 1044.67
   477.1 1038.64   483.7  1038.4   492.1 1038.68   551.9 1042.12   620.2  1049.3
   639.7 1054.67   659.2 1065.21   688.5  1076.6   825.1 1111.96   844.6 1120.16
   854.3 1121.67   873.8 1129.36   883.6 1131.24   903.1 1139.48   912.9 1141.54
#Mann= 3 , 0 , 0
       0      .1       0   477.1    .045       0   492.1      .1       0
Bank Sta=477.1,492.1
XS Rating Curve= 0 ,0
Exp/Cntr=0.3,0.1

Type RM Length L Ch R = 1 ,23224.6 ,566.347,576.286,587.328
XS GIS Cut Line= 3
      1823726.84      360912.756     1824173.024      361031.001
     1824624.343      361078.752
#Sta/Elev= 30
       0 1109.58     9.8 1106.85    29.5 1094.95    49.1  1086.7    58.9 1081.22
    98.2 1065.45   127.7 1056.79     275 1041.95   422.3 1040.53   474.3 1037.49
   489.3 1036.52   500.2 1035.97   519.5 1036.62   538.8 1039.51   548.5 1042.63
   577.5 1052.76   587.1 1057.78   606.4 1064.51   625.7 1074.85   635.4 1077.18
   654.7 1087.99   683.7 1099.58   693.3 1101.78   712.6 1109.84   741.6 1119.41
   760.9 1124.63   780.2 1132.36   847.8 1147.87   886.5 1163.07   915.4 1176.02
#Mann= 3 , 0 , 0
       0      .1       0   474.3    .045       0   489.3      .1       0
Bank Sta=474.3,489.3
XS Rating Curve= 0 ,0
Exp/Cntr=0.3,0.1

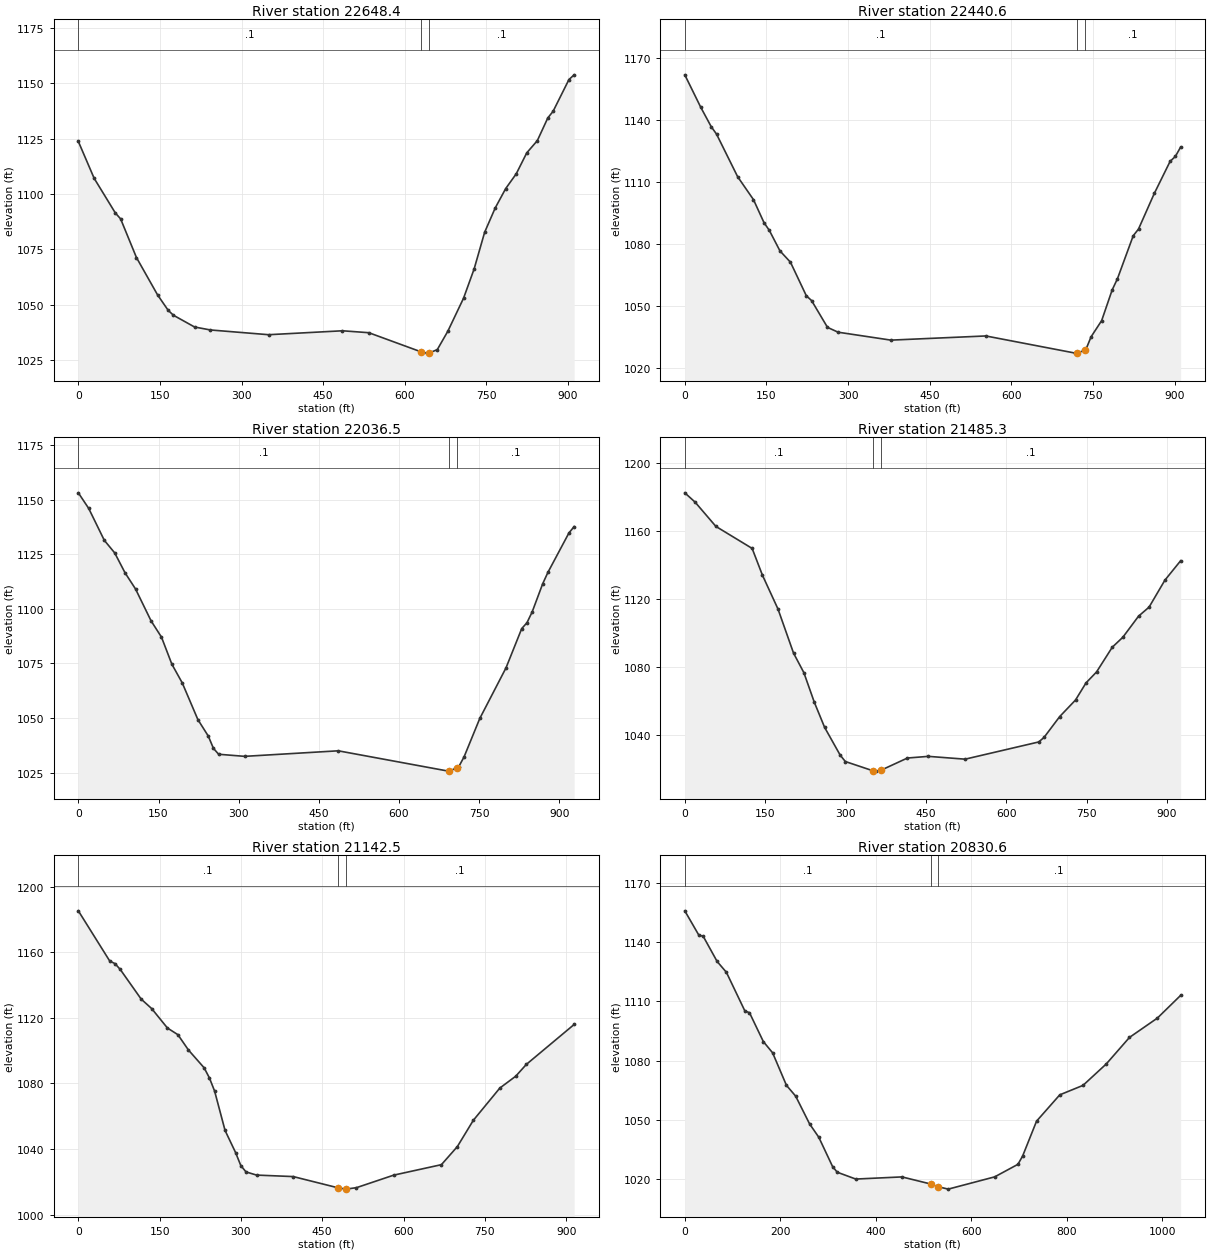
Type RM Length L Ch R = 1 ,22648.4 ,207.732,207.73,207.728
XS GIS Cut Line= 3
       1823586.9      361173.891     1823949.597       361450.88
     1824317.976       361717.53
#Sta/Elev= 30
       0 1123.71    29.1 1107.04      68 1091.41    77.7 1088.74   106.8 1071.28
   145.6 1054.41   165.1 1047.44   174.8 1045.21   213.6 1039.91   242.7 1038.57
   349.6 1036.43   485.4  1038.2   533.8 1037.33     629 1028.76   640.2 1028.11
     644 1028.11   659.6 1029.69   678.9 1037.97   707.9 1052.94   727.3 1066.13
   746.6 1082.68     766 1093.65   785.3 1102.42   804.7  1109.1     824 1118.55
   843.4 1124.06   862.7 1134.33   872.4 1137.32   901.5 1151.65   911.1 1153.79
#Mann= 3 , 0 , 0
       0      .1       0     629    .045       0     644      .1       0
#XS Ineff= 2 , 0
          485.39 1037.87
Permanent Ineff=
       F       F
Bank Sta=629,644
XS Rating Curve= 0 ,0
Exp/Cntr=0.3,0.1

Type RM Length L Ch R = 1 ,22440.6 ,393.359,404.101,414.844
XS GIS Cut Line= 3
     1823403.648      361297.017     1823766.345      361574.006
     1824134.724      361840.656
#Sta/Elev= 30
       0 1161.83    29.1 1146.24    48.5 1136.76    58.3 1133.15    97.1 1112.53
   126.2 1101.44   145.6 1090.27   155.4 1086.53   174.8 1076.66   194.2 1071.15
   223.3 1054.93     233 1052.59   262.2 1039.64   281.6  1037.3   378.7 1033.46
   553.1 1035.48   717.6 1027.17   719.8 1027.17   734.8 1028.52     737 1028.92
   746.6 1035.08     766 1042.91   785.3 1057.74     795 1063.16     824 1083.97
   833.7  1087.2   862.7 1104.43   891.8 1119.97   901.5 1122.36   911.1 1126.88
#Mann= 3 , 0 , 0
       0      .1       0   719.8    .045       0   734.8      .1       0
Bank Sta=719.8,734.8
XS Rating Curve= 0 ,0
Exp/Cntr=0.3,0.1

Type RM Length L Ch R = 1 ,22036.5 ,556.2,551.243,546.285
XS GIS Cut Line= 3
     1823373.134      361354.721     1823577.556      361785.118
     1823780.921        362187.9
#Sta/Elev= 30
       0 1153.17    19.4 1146.03    48.6 1131.41    68.1 1125.63    87.5 1116.48
     107 1109.13   136.1 1094.51   155.6 1087.04     175 1074.66   194.5 1066.05
   223.7 1049.26   243.1 1041.74   252.8 1036.09   262.5 1033.39   311.2 1032.43
   486.3 1034.97   692.3 1025.66   692.9 1025.68   707.9 1027.05   711.9 1027.74
   721.7 1032.17   751.1 1049.78   800.2 1072.98   829.6 1090.97   839.4 1093.65
   849.2 1098.64   868.8 1111.49   878.6 1116.72   917.9 1134.78   927.7 1137.71
#Mann= 3 , 0 , 0
       0      .1       0   692.9    .045       0   707.9      .1       0
Bank Sta=692.9,707.9
XS Rating Curve= 0 ,0
Exp/Cntr=0.3,0.1

Type RM Length L Ch R = 1 ,21485.3 ,341.751,342.787,343.822
XS GIS Cut Line= 3
     1822909.901      361748.333     1823183.598      362086.411
     1823483.283      362474.883
#Sta/Elev= 30
       0 1182.42    19.3 1176.93      58 1162.69   125.7 1149.75     145 1133.96
     174 1114.11     203 1088.21   222.3 1076.71   241.7  1059.4     261 1044.57
     290 1028.29   299.7 1024.49   351.6 1019.02   357.6 1018.85   366.6 1019.43
   415.6 1026.55   454.6 1027.53   523.3 1025.88   660.7 1035.99   670.5 1038.62
   699.9 1050.92   729.4 1060.65     749 1070.71   768.6 1077.12     798 1091.68
   817.7 1097.52   847.1 1109.94   866.7 1115.24   896.2 1131.06   925.6  1142.5
#Mann= 3 , 0 , 0
       0      .1       0   351.6    .045       0   366.6      .1       0
Bank Sta=351.6,366.6
XS Rating Curve= 0 ,0
Exp/Cntr=0.3,0.1

Type RM Length L Ch R = 1 ,21142.5 ,310.704,311.898,306.378
XS GIS Cut Line= 3
     1822610.016      361950.172     1822922.003      362280.635
     1823202.971      362645.229
#Sta/Elev= 30
       0 1185.34      58 1154.67    67.7 1153.12    77.4 1149.54     116 1131.45
   135.4 1125.66   164.4 1113.82   183.7 1109.75   203.1 1100.43   232.1 1089.54
   241.7 1083.47   251.4 1075.37   270.7 1051.32   290.1 1037.84   299.8 1029.86
   309.4    1026   328.8 1024.07   396.5 1023.16   479.1 1016.31   493.6  1015.5
   494.1 1015.51   513.2  1016.4   581.8 1024.03   669.9 1030.43   699.3 1041.46
   728.7 1057.48   777.7 1077.19     807 1084.41   826.6 1091.62   914.8    1116
#Mann= 3 , 0 , 0
       0      .1       0   479.1    .045       0   494.1      .1       0
Bank Sta=479.1,494.1
XS Rating Curve= 0 ,0
Exp/Cntr=0.3,0.1

Type RM Length L Ch R = 1 ,20830.6 ,418.789,400,391.695
XS GIS Cut Line= 3
     1822395.342      362047.581     1822689.179      362479.657
     1823086.522      362808.655
#Sta/Elev= 30
       0    1156      29 1143.82    38.7 1143.01    67.7  1130.3    87.1 1124.81
   125.8  1105.2   135.5 1104.29   164.5 1089.64   183.9 1083.95   212.9 1067.43
   232.2 1061.95   261.3 1047.88   280.6  1041.1   309.6 1026.16   319.3 1023.34
     358 1019.87   454.8 1020.96     515 1017.36     530 1016.01   551.7 1014.76
   649.1 1020.99   697.7 1027.35   707.5 1031.55   736.7 1049.26   785.3 1062.61
     834 1067.42   882.7 1078.29   931.3 1091.76   989.7 1101.56  1038.4 1113.08
#Mann= 3 , 0 , 0
       0      .1       0     515    .045       0     530      .1       0
Bank Sta=515,530
XS Rating Curve= 0 ,0
Exp/Cntr=0.3,0.1