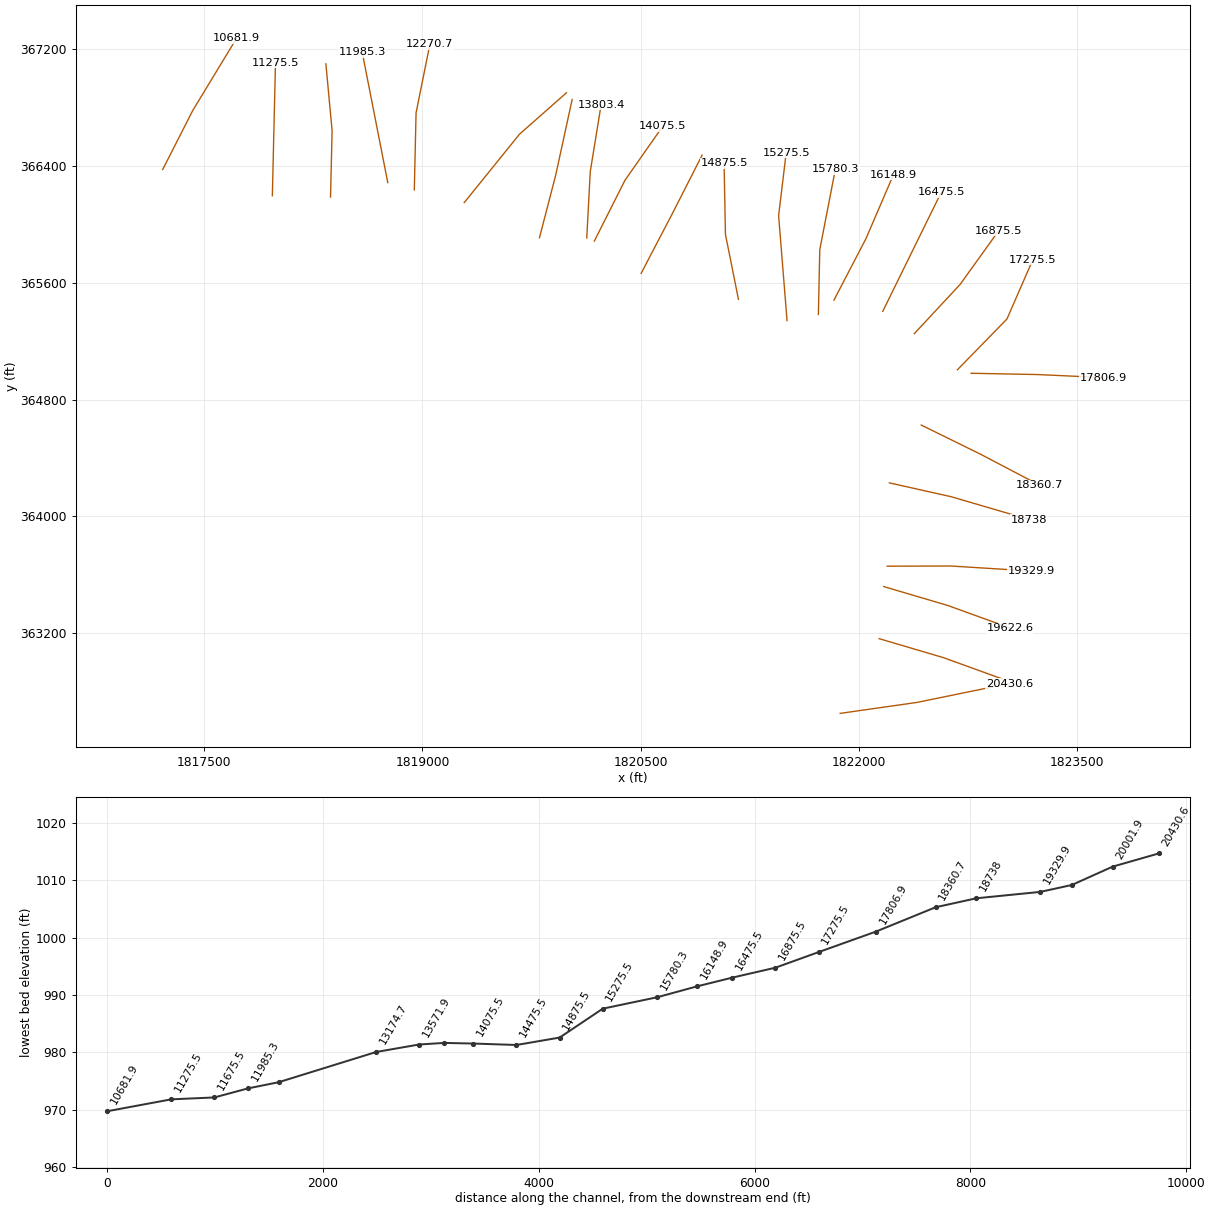
HEC-RAS study WhtdyCrk.prj: WhtdyCrk

--- WhtdyCrk.g01 (geometry) --- (continued)

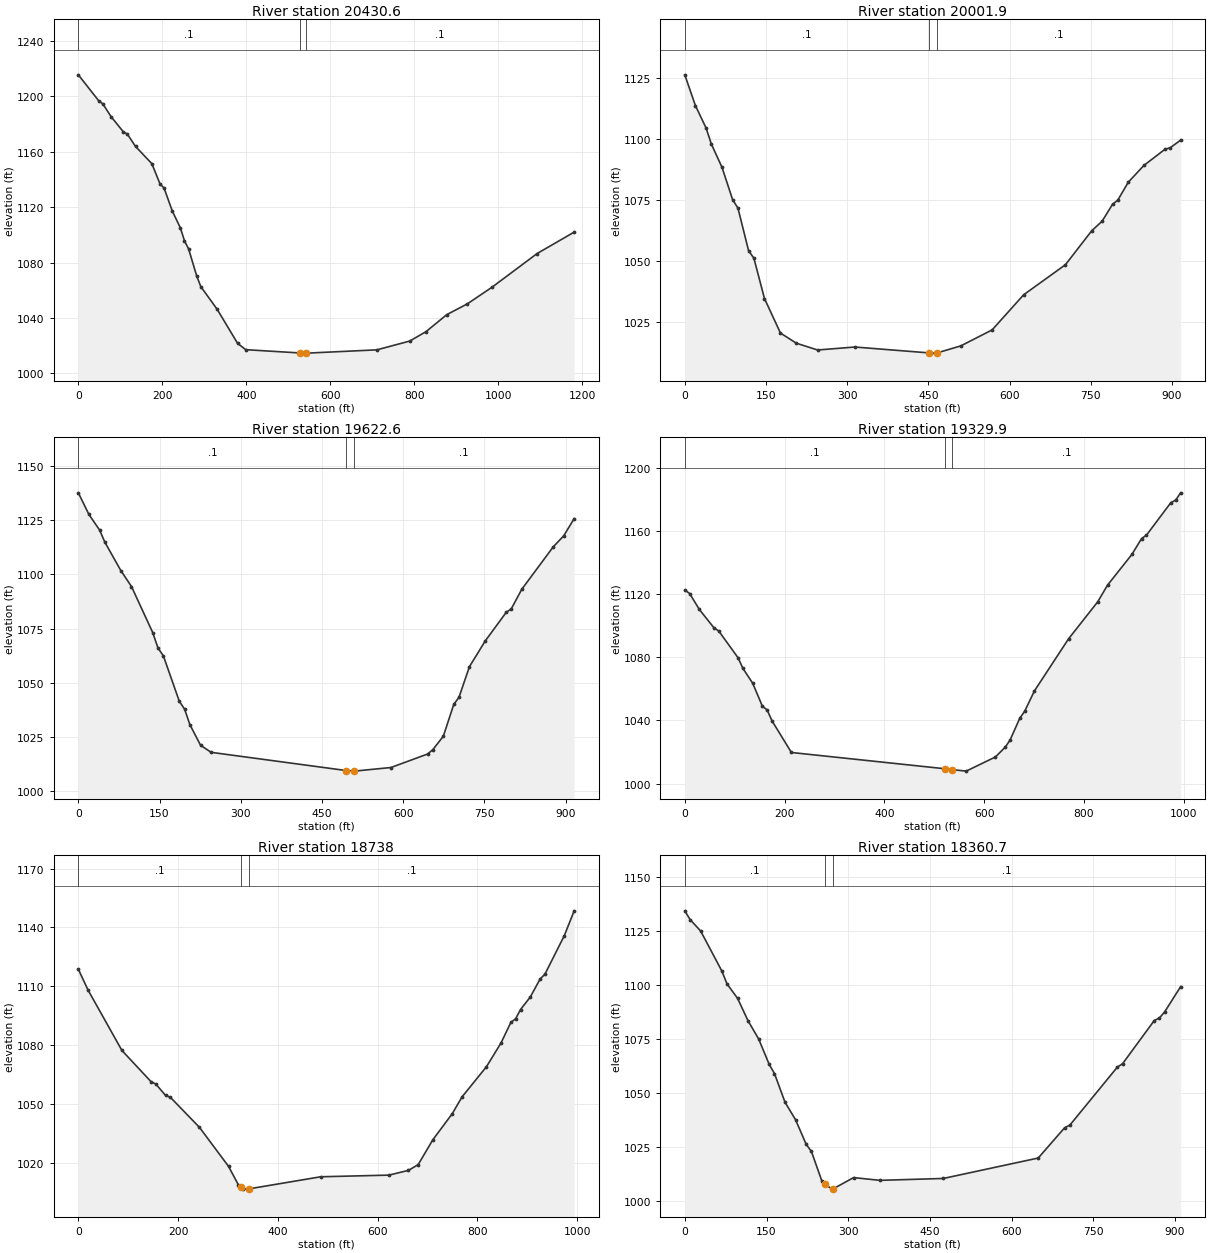
Type RM Length L Ch R = 1 ,20430.6 ,436.514,428.734,415.68
XS GIS Cut Line= 3
     1821871.132      362653.334     1822400.446      362728.504
     1823033.056      362857.564
#Sta/Elev= 30
       0 1215.49    48.6 1196.74    58.3 1194.58    77.8 1185.37   106.9 1174.44
   116.6 1172.73   136.1 1163.83     175 1151.38   194.4 1136.79   204.1 1133.75
   223.6 1117.28     243 1104.96   252.7 1095.68   262.5 1089.85   281.9 1070.21
   291.6 1062.62   330.5 1046.26   379.1 1021.71   398.5 1017.13   527.1 1014.77
   542.1 1014.65   544.4 1014.64   710.7 1017.01     789 1023.36   828.1 1030.24
     877 1042.41   925.9 1050.17   984.6 1062.17  1092.2 1086.53  1180.3 1101.98
#Mann= 3 , 0 , 0
       0      .1       0   527.1    .045       0   542.1      .1       0
Bank Sta=527.1,542.1
XS Rating Curve= 0 ,0
Exp/Cntr=0.3,0.1

Type RM Length L Ch R = 1 ,20001.9 ,380.758,379.219,378.967
XS GIS Cut Line= 3
     1822138.884       363164.36     1822581.548      363034.297
     1823009.039      362880.084
#Sta/Elev= 30
       0 1126.15    19.6 1113.57    39.3 1104.41    49.1 1097.81    68.7 1088.33
    88.3 1075.12    98.2 1071.61   117.8 1054.24   127.6 1051.17   147.2 1034.65
   176.7 1020.55   206.1 1016.39   245.4 1013.62   314.1 1014.84   450.6 1012.44
   461.4 1012.34   465.6 1012.41   509.7 1015.29   567.7 1021.85   625.8 1036.19
   703.1 1048.51   751.5 1062.35   770.8 1066.29   790.1 1073.23   799.8 1074.92
   819.1 1082.24   848.1 1089.12   886.8 1095.69   896.5 1096.32   915.8 1099.44
#Mann= 3 , 0 , 0
       0      .1       0   450.6    .045       0   465.6      .1       0
Bank Sta=450.6,465.6
XS Rating Curve= 0 ,0
Exp/Cntr=0.3,0.1

Type RM Length L Ch R = 1 ,19622.6 ,285.96,292.719,299.479
XS GIS Cut Line= 3
     1822170.117      363520.717     1822612.781      363390.654
     1823040.272      363236.442
#Sta/Elev= 30
       0 1137.72    19.6 1127.71    39.3 1120.52    49.1 1114.86    78.5  1101.8
    98.2 1094.42   137.4 1073.16   147.2 1065.98   157.1 1062.37   186.5 1041.42
   196.3 1037.76   206.1  1030.6   225.8 1021.07   245.4 1017.82   494.7 1009.41
   509.7 1009.14   577.4 1010.81   645.1 1017.05   654.8 1019.08   674.1 1025.24
   693.4 1039.93   703.1 1043.29   722.4 1057.41   751.5 1069.26   790.1 1082.43
   799.8 1084.18   819.1 1093.18   877.2 1112.78   896.5 1117.85   915.8 1125.82
#Mann= 3 , 0 , 0
       0      .1       0   494.7    .045       0   509.7      .1       0
Bank Sta=494.7,509.7
XS Rating Curve= 0 ,0
Exp/Cntr=0.3,0.1

Type RM Length L Ch R = 1 ,19329.9 ,595.42,591.965,588.51
XS GIS Cut Line= 3
     1822194.096      363660.116     1822631.142      363661.269
     1823186.809      363626.899
#Sta/Elev= 30
       0 1122.53     9.7 1120.33    29.1 1110.26    58.3 1098.68      68 1096.62
   106.8 1079.66   116.5 1072.93     136  1063.6   155.4 1049.11   165.1 1046.62
   174.8 1039.75   213.7 1019.73   521.1 1009.45   536.1 1008.88     564 1007.94
   622.6  1016.9   642.2 1023.08   651.9 1027.58   671.5 1041.45   681.2 1045.81
   700.8 1058.71   769.1 1091.62   827.7  1115.1   847.3 1125.63   896.1 1145.05
   915.6 1155.12   925.4 1157.26   974.2 1177.82     984 1179.46   993.8 1184.03
#Mann= 3 , 0 , 0
       0      .1       0   521.1    .045       0   536.1      .1       0
Bank Sta=521.1,536.1
XS Rating Curve= 0 ,0
Exp/Cntr=0.3,0.1

Type RM Length L Ch R = 1 ,18738   ,382.721,377.287,371.853
XS GIS Cut Line= 3
     1822209.358      364229.851     1822635.934      364134.752
     1823170.398      363978.886
#Sta/Elev= 30
       0 1118.77    19.4 1108.18    87.4 1077.39   145.7 1061.54   155.4 1060.29
   174.8 1054.53   184.5 1053.56   242.8 1038.27   301.1  1018.4   320.5 1009.15
   326.1 1007.81   330.2 1006.83   341.1 1006.93   485.9 1013.12   622.6 1013.96
   661.7 1016.37   681.2 1019.33   710.5 1031.93   749.6 1045.28   769.1 1053.79
     818 1069.13   847.3 1081.26   866.8 1091.65   876.6  1093.6   886.3 1098.24
   905.9 1104.62   925.4 1113.72   935.2 1116.24   974.2 1135.92   993.8 1148.48
#Mann= 3 , 0 , 0
       0      .1       0   326.1    .045       0   341.1      .1       0
Bank Sta=326.1,341.1
XS Rating Curve= 0 ,0
Exp/Cntr=0.3,0.1

Type RM Length L Ch R = 1 ,18360.7 ,543.459,553.745,564.032
XS GIS Cut Line= 3
     1822428.055      364625.461      1822836.88      364425.322
     1823240.194      364214.767
#Sta/Elev= 30
       0 1134.22     9.7 1130.19    29.1 1124.87    67.8 1106.43    77.5 1100.37
    96.8 1093.71   116.2 1083.22   135.6 1074.84     155 1063.02   164.6 1058.84
     184 1045.52   203.4 1037.38   222.8 1026.05   232.4 1022.74   251.8  1008.9
   256.6 1007.49   271.2 1005.27   271.6 1005.31   309.9 1010.61   358.3 1009.34
   474.5 1010.21   648.8 1019.68   697.2 1033.69   706.9 1034.94     794 1061.79
   803.7  1063.4   861.8 1083.39   871.4 1084.59   881.1 1087.48   910.2 1099.09
#Mann= 3 , 0 , 0
       0      .1       0   256.6    .045       0   271.6      .1       0
Bank Sta=256.6,271.6
XS Rating Curve= 0 ,0
Exp/Cntr=0.3,0.1

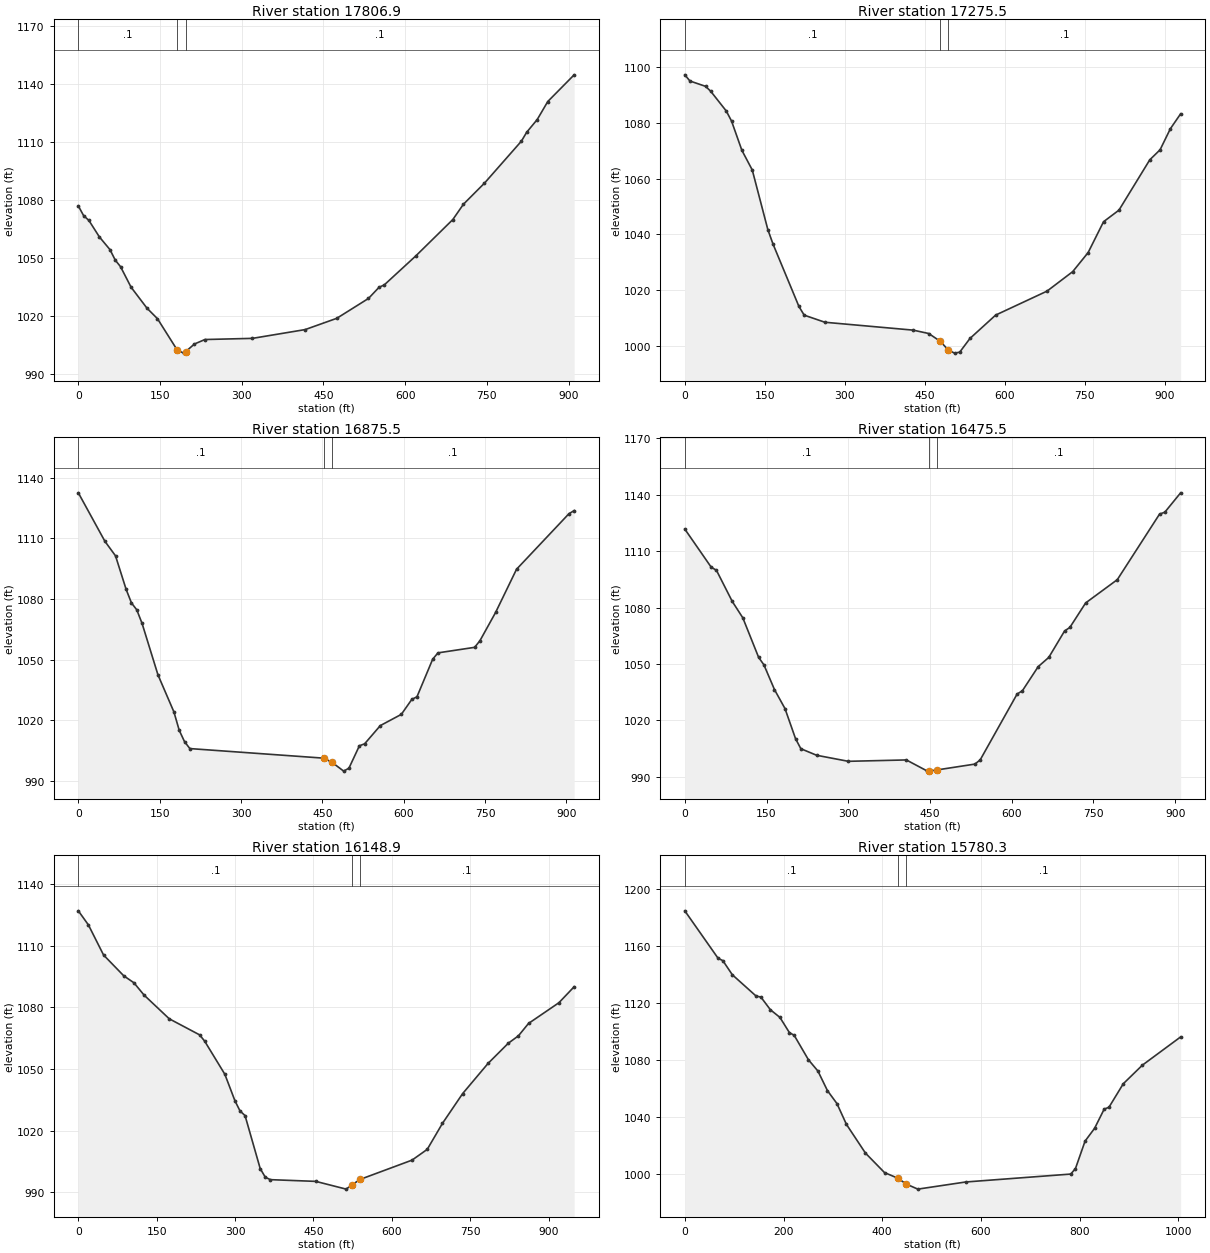
Type RM Length L Ch R = 1 ,17806.9 ,510.661,531.459,559.899
XS GIS Cut Line= 3
     1822770.815      364979.596     1823225.916      364970.853
     1823680.421      364950.342
#Sta/Elev= 30
       0    1077     9.7    1072    19.4 1069.52    38.7 1060.99    58.1 1054.45
    67.8 1049.02    77.5 1045.65    96.8 1035.07   125.9 1024.28   145.3 1018.79
   181.9 1002.46   193.7 1001.03   196.9 1001.77   213.1 1005.73   232.4 1008.05
   319.6 1008.65   416.4 1013.18   474.5 1019.01   532.6 1029.25     552    1035
   561.7 1036.26   619.7 1051.26   687.5 1069.99   706.9 1077.87   745.6 1088.78
   813.4 1110.46     823 1115.02   842.4  1121.6   861.8 1130.91   910.2 1144.68
#Mann= 3 , 0 , 0
       0      .1       0   181.9    .045       0   196.9      .1       0
Bank Sta=181.9,196.9
XS Rating Curve= 0 ,0
Exp/Cntr=0.3,0.1

Type RM Length L Ch R = 1 ,17275.5 ,399.414,400,395.181
XS GIS Cut Line= 3
     1822676.498      365003.419     1823017.149      365350.695
     1823194.934      365756.599
#Sta/Elev= 30
       0 1097.17     9.7 1094.95    38.9 1093.05    48.6 1091.28    77.8  1084.2
    87.6 1080.62     107 1070.13   126.5 1063.07   155.7 1041.71   165.4 1036.53
     214 1014.17   223.8 1011.07   262.7 1008.52   428.1  1005.7   457.3 1004.49
     479 1001.69     494  998.59   505.7  997.46   515.4   997.8   534.6 1002.71
   582.8 1011.09   679.1 1019.67   727.3 1026.66   756.2 1033.49   785.1 1044.54
     814 1048.69   871.8 1066.73   891.1 1070.32   910.3 1077.83   929.6  1083.2
#Mann= 3 , 0 , 0
       0      .1       0     479    .045       0     494      .1       0
Bank Sta=479,494
XS Rating Curve= 0 ,0
Exp/Cntr=0.3,0.1

Type RM Length L Ch R = 1 ,16875.5 ,393.374,400,403.771
XS GIS Cut Line= 3
     1822380.826      365250.964      1822695.24      365587.305
     1822961.079      365955.389
#Sta/Elev= 30
       0 1132.61      49 1108.61    68.6 1101.39    88.2 1084.75      98 1078.07
   107.8 1074.65   117.6 1067.89   146.9 1042.42   176.3 1024.08   186.1 1014.96
   195.9 1009.33   205.7 1005.92   452.9 1001.17   467.9  999.11   489.4  994.75
   499.1  996.21   518.4 1007.31     528 1008.27     557 1017.31   595.7 1022.86
     615 1030.25   624.6 1031.59   653.6 1050.21   663.3 1053.33   730.9 1056.07
   740.6  1059.3   769.6 1073.35   808.2 1094.74   904.8 1122.24   914.5 1123.81
#Mann= 3 , 0 , 0
       0      .1       0   452.9    .045       0   467.9      .1       0
Bank Sta=452.9,467.9
XS Rating Curve= 0 ,0
Exp/Cntr=0.3,0.1

Type RM Length L Ch R = 1 ,16475.5 ,334.274,326.605,327.742
XS GIS Cut Line= 3
     1822163.611      365403.131     1822365.025      365811.124
     1822566.438      366219.116
#Sta/Elev= 30
       0 1121.76    48.4 1101.51    58.1 1099.83    87.1 1083.28   106.5 1074.54
   135.5 1053.53   145.2 1049.55   164.6 1036.39   183.9 1026.27   203.3 1010.24
     213 1004.94     242 1001.45   300.1  998.24   406.6  998.97   445.3  993.02
   447.5  993.03   462.5  993.64   532.4  996.76   542.1  998.98   609.9 1034.02
   619.6 1035.77   648.6 1048.59     668  1053.5     697 1067.56   706.7 1069.44
   735.7 1082.48   793.8 1094.86   871.3 1129.71     881 1130.74     910 1141.04
#Mann= 3 , 0 , 0
       0      .1       0   447.5    .045       0   462.5      .1       0
Bank Sta=447.5,462.5
XS Rating Curve= 0 ,0
Exp/Cntr=0.3,0.1

Type RM Length L Ch R = 1 ,16148.9 ,348.84,368.612,374.949
XS GIS Cut Line= 3
     1821828.358      365480.196     1822047.962      365900.028
     1822236.535      366336.216
#Sta/Elev= 30
       0 1126.91    19.3 1120.05    48.3 1105.41      87 1095.28   106.4  1091.9
   125.7 1085.95     174 1074.38   232.1 1066.56   241.7 1063.54   280.4  1047.4
   299.8 1034.45   309.4 1029.57   319.1 1027.28   348.1  1001.5   357.8  997.31
   367.4  996.11   454.5  995.27   512.6   991.5   524.3  993.68   539.3  996.23
   638.7 1005.61   667.8 1010.85   696.9 1023.49   735.6 1037.99   784.1 1052.64
   822.9 1062.48   842.3 1066.08   861.7 1072.12   919.9 1082.21     949 1089.98
#Mann= 3 , 0 , 0
       0      .1       0   524.3    .045       0   539.3      .1       0
Bank Sta=524.3,539.3
XS Rating Curve= 0 ,0
Exp/Cntr=0.3,0.1

Type RM Length L Ch R = 1 ,15780.3 ,499.945,504.783,504.454
XS GIS Cut Line= 3
      1821721.19      365381.678     1821730.736       365824.68
     1821838.005       366375.69
#Sta/Elev= 30
       0 1184.75    67.4  1151.5    77.1 1149.81    96.3 1139.92   144.5 1124.97
   154.1  1124.3   173.4 1115.39   192.7 1110.03   211.9 1099.37   221.6 1097.47
   250.5 1080.31   269.7 1072.41     289 1058.67   308.2 1049.63   327.5    1035
     366 1014.87   404.6 1001.21   432.9  997.08   447.9  993.27   472.1  989.61
   568.9  994.61   781.9 1000.17   791.5 1004.07   810.9 1023.28   830.2 1032.24
   849.6  1045.7   859.3 1047.01   888.3 1063.49     927 1076.53  1004.5 1096.33
#Mann= 3 , 0 , 0
       0      .1       0   432.9    .045       0   447.9      .1       0
Bank Sta=432.9,447.9
XS Rating Curve= 0 ,0
Exp/Cntr=0.3,0.1

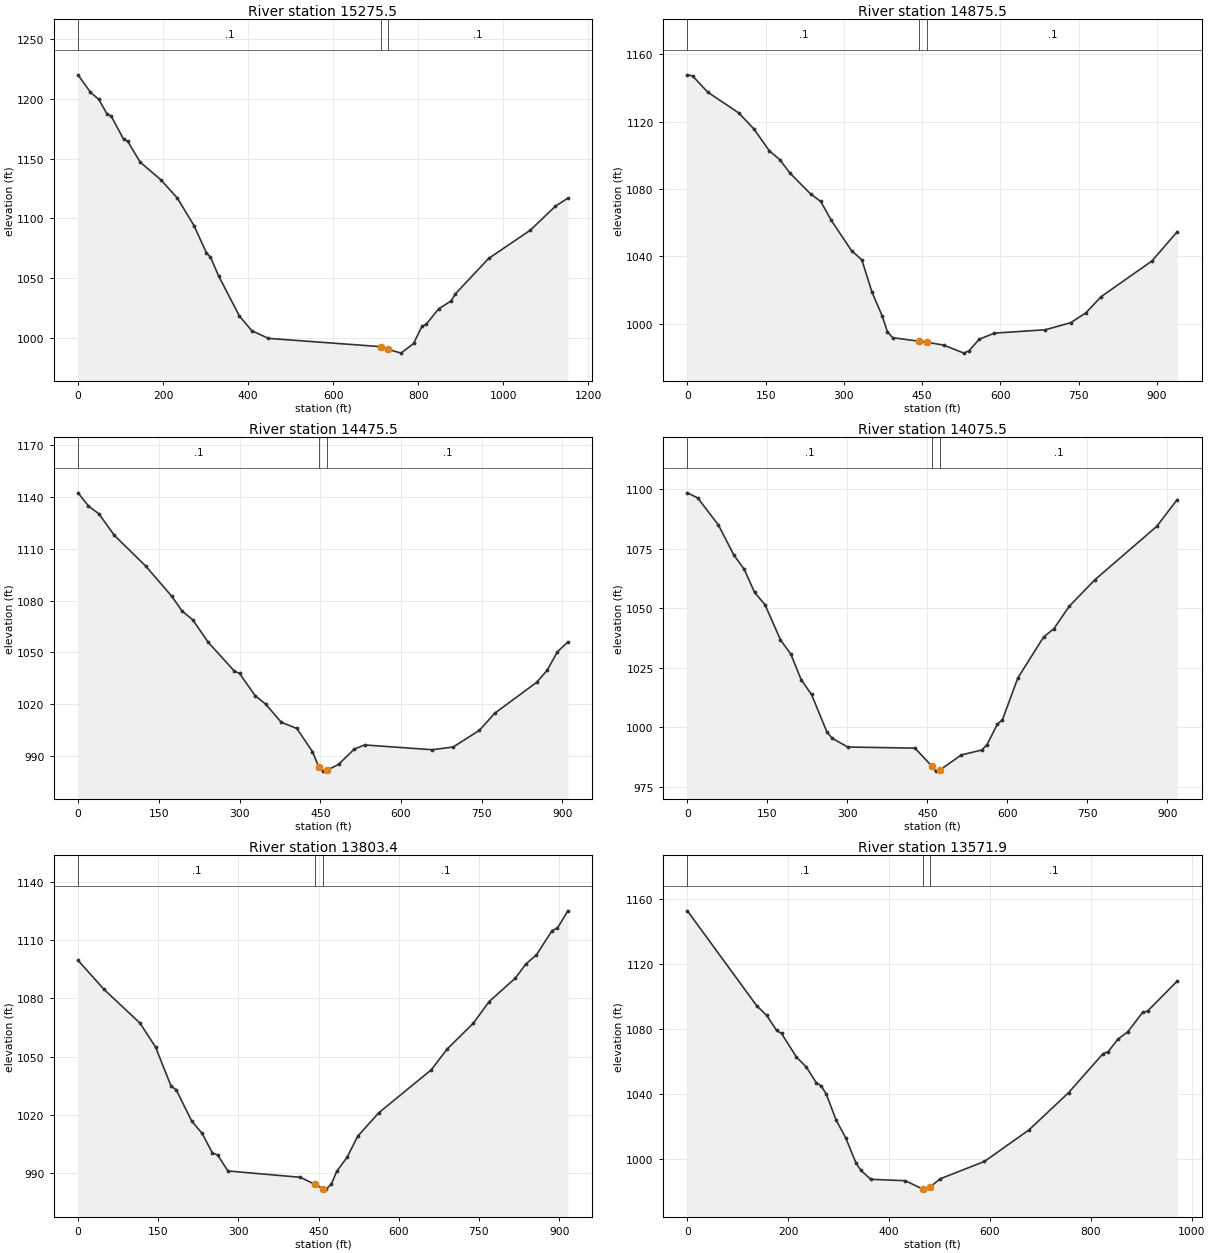
Type RM Length L Ch R = 1 ,15275.5 ,396.703,400,403.543
XS GIS Cut Line= 3
     1821505.763      365339.786     1821447.916      366058.134
     1821499.866      366486.729
#Sta/Elev= 30
       0 1219.93    29.2 1205.38    48.7  1199.5    68.2 1187.26    77.9  1185.5
   107.1 1166.26   116.9  1164.4   146.1 1147.08   194.8 1132.34   233.7 1117.02
   272.7 1094.14   301.9 1071.46   311.6 1067.73   331.1 1051.81   379.8 1018.48
     409 1006.28     448  999.92   713.2     993   728.2   990.9   759.9  987.62
   789.4  995.71     809 1009.98   818.8 1011.61   848.2 1024.52   877.7 1031.23
   887.5 1037.03     966 1066.68  1064.1 1090.28    1123 1110.29  1152.4 1116.97
#Mann= 3 , 0 , 0
       0      .1       0   713.2    .045       0   728.2      .1       0
Bank Sta=713.2,728.2
XS Rating Curve= 0 ,0
Exp/Cntr=0.3,0.1

Type RM Length L Ch R = 1 ,14875.5 ,416.046,400,388.523
XS GIS Cut Line= 3
     1821171.782      365485.765     1821082.415      365929.216
     1821073.136      366415.863
#Sta/Elev= 30
       0 1147.79     9.8 1147.17    39.3 1137.44    98.3  1125.2   127.8 1115.57
   157.3 1102.57     177 1097.49   196.7 1089.46     236 1077.13   255.7 1072.61
   275.4 1061.61   314.7 1043.39   334.4 1037.97     354  1018.7   373.7 1004.47
   383.5  995.24   393.4  991.75   444.9  989.63   459.9  989.03   491.3  987.34
   530.2  982.59     540  984.02   559.4  990.83   588.7  994.46     686  996.46
   734.7 1000.63   763.9 1006.49   793.1  1016.1   890.4 1037.25   939.1 1054.66
#Mann= 3 , 0 , 0
       0      .1       0   444.9    .045       0   459.9      .1       0
Bank Sta=444.9,459.9
XS Rating Curve= 0 ,0
Exp/Cntr=0.3,0.1

Type RM Length L Ch R = 1 ,14475.5 ,399.654,400,396.835
XS GIS Cut Line= 3
     1820503.152      365663.382     1820714.586      366066.121
      1820922.04      366471.335
#Sta/Elev= 30
       0 1142.41    19.4 1134.77    38.7 1130.26    67.7 1117.72   125.8 1099.99
   174.2  1082.5   193.6 1073.87   212.9 1068.95     242 1055.84   290.3 1039.26
     300 1037.85   329.1 1024.98   348.4 1020.14   377.4 1009.63   406.5 1005.99
   435.5  992.59   447.4  983.63   454.9   981.3   462.4   981.8   483.9  985.19
     513  994.01   532.4  996.46   658.3  993.68     697  995.27   745.4 1004.86
   774.5 1014.88     852  1032.7   871.4 1039.63   890.7 1050.43   910.1 1056.08
#Mann= 3 , 0 , 0
       0      .1       0   447.4    .045       0   462.4      .1       0
Bank Sta=447.4,462.4
XS Rating Curve= 0 ,0
Exp/Cntr=0.3,0.1

Type RM Length L Ch R = 1 ,14075.5 ,260.809,272.033,283.99
XS GIS Cut Line= 3
     1820181.536      365884.132     1820391.788      366299.596
     1820652.557      366670.163
#Sta/Elev= 30
       0 1098.44    19.4  1096.3    58.2 1084.93    87.3 1072.25   106.7 1066.29
   126.1 1056.58   145.5 1051.48   174.6  1036.7     194  1030.7   213.4 1019.96
   232.8 1013.74   261.9   997.9   271.6  995.34   300.7  991.68   426.8  991.21
   458.1  983.74   465.6  981.55   473.1  981.96   513.8  988.34   552.4  990.44
     562   992.7   581.3 1001.22     591 1003.19   619.9 1020.74   668.1 1037.88
   687.4 1041.37   716.3 1050.83   764.5 1061.97   880.2 1084.33   918.8 1095.62
#Mann= 3 , 0 , 0
       0      .1       0   458.1    .045       0   473.1      .1       0
Bank Sta=458.1,473.1
XS Rating Curve= 0 ,0
Exp/Cntr=0.3,0.1

Type RM Length L Ch R = 1 ,13803.4 ,235.359,231.555,229.811
XS GIS Cut Line= 3
     1820129.262      365905.417     1820153.403      366359.218
     1820227.764      366815.141
#Sta/Elev= 30
       0 1099.58    48.3 1084.69     116  1067.2     145 1054.86     174 1034.81
   183.7 1032.84   212.7  1016.7   232.1  1010.4   251.4 1000.31   261.1  999.28
   280.4  991.02   415.8  987.76   443.4  984.09   458.4  981.89   464.3  981.66
   474.1   984.4   483.9  990.78   503.6  998.22   523.2 1008.94   562.6 1021.01
   660.8 1043.16   690.3  1053.8   739.5 1067.19     769 1078.31   818.1 1090.44
   837.8 1097.69   857.4 1102.37   886.9 1114.94   896.7 1116.19   916.4  1125.1
#Mann= 3 , 0 , 0
       0      .1       0   443.4    .045       0   458.4      .1       0
Bank Sta=443.4,458.4
XS Rating Curve= 0 ,0
Exp/Cntr=0.3,0.1

Type RM Length L Ch R = 1 ,13571.9 ,406.287,397.155,389.402
XS GIS Cut Line= 3
     1819804.357      365906.956     1819915.808      366334.839
     1820028.853       366851.96
#Sta/Elev= 30
       0 1152.88   137.6 1094.33   157.2 1088.47   176.9 1079.18   186.7 1077.29
   216.2 1062.77   235.8 1056.67   255.5    1047   265.3 1044.99   275.1 1040.14
   294.8 1024.09   314.4 1012.69   334.1  997.66   343.9     993   363.6  987.44
   432.3  986.56   466.5  981.44   471.6  981.38   481.5  982.71     501   987.7
   589.2  998.44   677.4 1017.87   755.8 1040.77   824.5 1064.93   834.3 1066.03
   853.9 1073.83   873.5 1078.39   902.9 1090.33   912.7 1091.11   971.5 1109.63
#Mann= 3 , 0 , 0
       0      .1       0   466.5    .045       0   481.5      .1       0
Bank Sta=466.5,481.5
XS Rating Curve= 0 ,0
Exp/Cntr=0.3,0.1

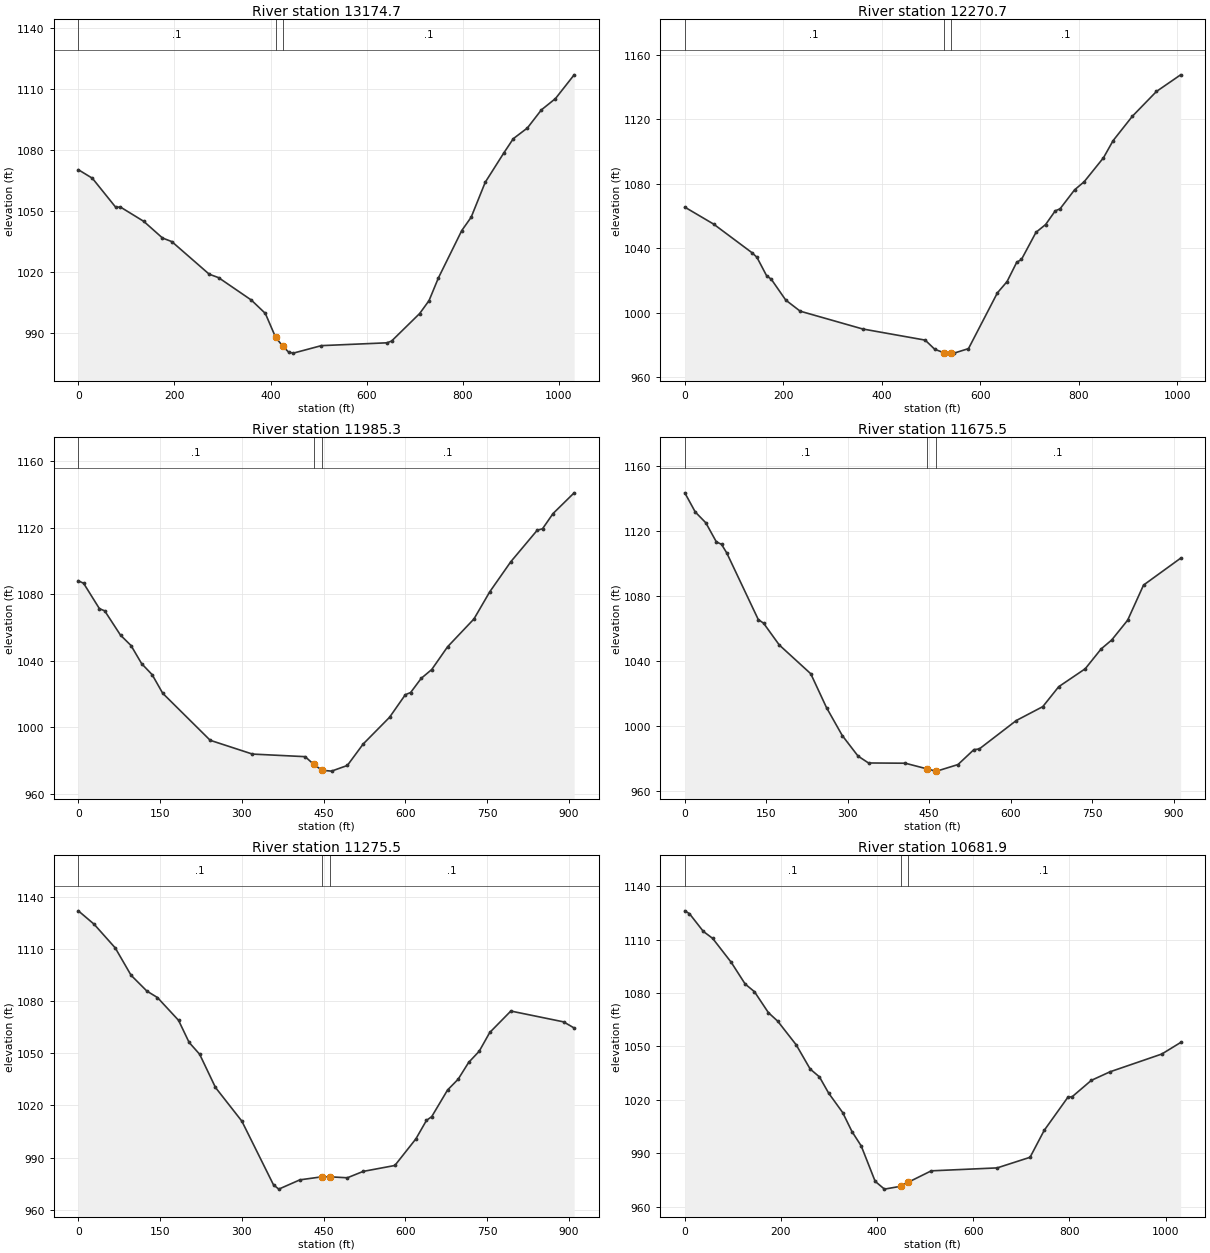
Type RM Length L Ch R = 1 ,13174.7 ,891.102,903.992,911.929
XS GIS Cut Line= 3
     1819287.211      366146.985     1819667.433      366615.262
     1819989.765      366898.125
#Sta/Elev= 30
       0 1070.43    29.2 1066.23    77.8 1051.93    87.6 1052.04   136.2 1044.99
   175.1  1036.8   194.6 1035.01   272.4 1018.96   291.9 1017.26     360 1006.23
   389.2  999.65   410.6  987.88   425.6  983.48   437.8  980.56   447.5  980.08
   505.9  983.77   642.2  985.16   651.9  986.01   710.4  999.58   729.9 1005.93
   749.4 1017.11   798.1 1040.47   817.6 1047.01   846.9 1064.23   885.9  1078.8
   905.3 1085.71   934.6 1090.97   963.8 1099.91   993.1 1105.47    1032 1117.17
#Mann= 3 , 0 , 0
       0      .1       0   410.6    .045       0   425.6      .1       0
Bank Sta=410.6,425.6
XS Rating Curve= 0 ,0
Exp/Cntr=0.3,0.1

Type RM Length L Ch R = 1 ,12270.7 ,279.437,285.402,294.535
XS GIS Cut Line= 3
     1818944.102       366233.82     1818956.128      366760.562
     1819051.309       367230.51
#Sta/Elev= 30
       0 1065.42    58.5 1054.89   136.6 1037.09   146.4  1034.3   165.9 1022.93
   175.6 1020.64   204.9 1007.74   234.2 1000.85     361  989.81   487.9   982.9
   507.4  977.19   525.3  975.15   540.3  974.86   546.5  974.82   575.8  977.61
   634.5 1012.22   654.1 1019.21   673.7 1031.18   683.4 1032.98   712.8 1049.77
   732.4 1054.63   751.9 1063.11   761.7 1064.38   791.1 1076.13   810.7  1081.2
   849.8 1096.05   869.4 1106.71   908.5 1121.83   957.4 1137.21  1006.4 1147.52
#Mann= 3 , 0 , 0
       0      .1       0   525.3    .045       0   540.3      .1       0
Bank Sta=525.3,540.3
XS Rating Curve= 0 ,0
Exp/Cntr=0.3,0.1

Type RM Length L Ch R = 1 ,11985.3 ,314.871,309.863,307.507
XS GIS Cut Line= 3
     1818761.673      366284.001      1818673.65      366730.405
     1818585.626      367176.809
#Sta/Elev= 30
       0 1088.23     9.7 1086.71    38.7 1071.46    48.4 1070.14    77.4 1055.54
    96.8 1049.25   116.2 1038.38   135.5 1031.75   154.9 1020.56     242  992.29
   319.5     984   416.3  982.44   432.2  977.77   447.2  974.27   464.7  973.74
   493.7  977.14   522.8  990.06   571.2 1006.13   600.2 1019.72   609.9 1021.03
   629.3 1029.55   648.6 1034.85   677.7 1048.54   726.1 1065.27   755.1  1081.6
   793.8 1099.72   842.2 1118.63   851.9  1119.5   871.3 1128.69     910 1141.13
#Mann= 3 , 0 , 0
       0      .1       0   432.2    .045       0   447.2      .1       0
Bank Sta=432.2,447.2
XS Rating Curve= 0 ,0
Exp/Cntr=0.3,0.1

Type RM Length L Ch R = 1 ,11675.5 ,400,400,397.349
XS GIS Cut Line= 3
     1818368.282      366184.841     1818379.096      366639.038
     1818336.267      367095.856
#Sta/Elev= 30
       0 1143.44    19.3 1131.64    38.7    1125      58 1113.32    67.7 1111.72
    77.3 1106.42   135.3 1065.46     145 1063.24     174  1049.8     232 1032.09
     261 1011.24     290  994.07     319  981.44   338.3  977.19     406  977.04
   446.8  973.49   461.8   972.2   464.1  972.17   503.1  976.22   532.4   985.4
   542.2  985.79   610.5 1003.32   659.3 1011.87   688.6 1024.13   737.4 1035.16
   766.7 1047.36   786.2 1052.88   815.5 1065.04   844.8 1086.67   913.1 1103.21
#Mann= 3 , 0 , 0
       0      .1       0   446.8    .045       0   461.8      .1       0
Bank Sta=446.8,461.8
XS Rating Curve= 0 ,0
Exp/Cntr=0.3,0.1

Type RM Length L Ch R = 1 ,11275.5 ,604.197,593.577,581.442
XS GIS Cut Line= 3
     1817968.379      366193.688     1817979.209      366648.559
      1817990.04       367103.43
#Sta/Elev= 30
       0 1131.77      29 1124.06    67.8 1110.43    96.8 1094.74   125.9 1085.64
   145.2 1081.94   183.9 1068.86   203.3 1056.16   222.7 1049.32   251.7 1030.26
   300.1 1010.91   358.2   974.3   367.9  971.84   406.6  977.17   447.5  978.94
   462.5   978.9   493.7  978.36   522.8  982.03   580.9  985.43   619.6 1000.76
   638.9 1011.33   648.6 1013.51   677.7 1028.83     697 1034.97   716.4 1044.67
   735.7 1051.07   755.1 1061.86   793.8 1074.18   890.6 1067.96     910 1064.43
#Mann= 3 , 0 , 0
       0      .1       0   447.5    .045       0   462.5      .1       0
Bank Sta=447.5,462.5
XS Rating Curve= 0 ,0
Exp/Cntr=0.3,0.1

Type RM Length L Ch R = 1 ,10681.9 ,208.9,206.423,205.462
XS GIS Cut Line= 3
     1817214.753      366373.322     1817421.601      366777.398
     1817722.253      367270.467
#Sta/Elev= 30
       0 1126.19     9.7 1124.59    38.6 1114.61      58 1110.69    96.6 1097.24
   125.6 1085.04   144.9 1080.74   173.9 1068.96   193.2  1064.2   231.8 1050.85
   260.8 1037.27   280.1 1032.85   299.4 1023.66   328.4 1012.81   347.7 1002.15
     367  994.04     396  974.15   415.3  969.77   448.7  971.35   463.7   973.5
   512.7  980.05   649.7   981.7   718.2  987.67   747.6 1002.79   796.5 1021.27
   806.3 1021.82   845.5 1030.88   884.6 1035.72   992.3 1045.71  1031.4 1052.19
#Mann= 3 , 0 , 0
       0      .1       0   448.7    .045       0   463.7      .1       0
Bank Sta=448.7,463.7
XS Rating Curve= 0 ,0
Exp/Cntr=0.3,0.1