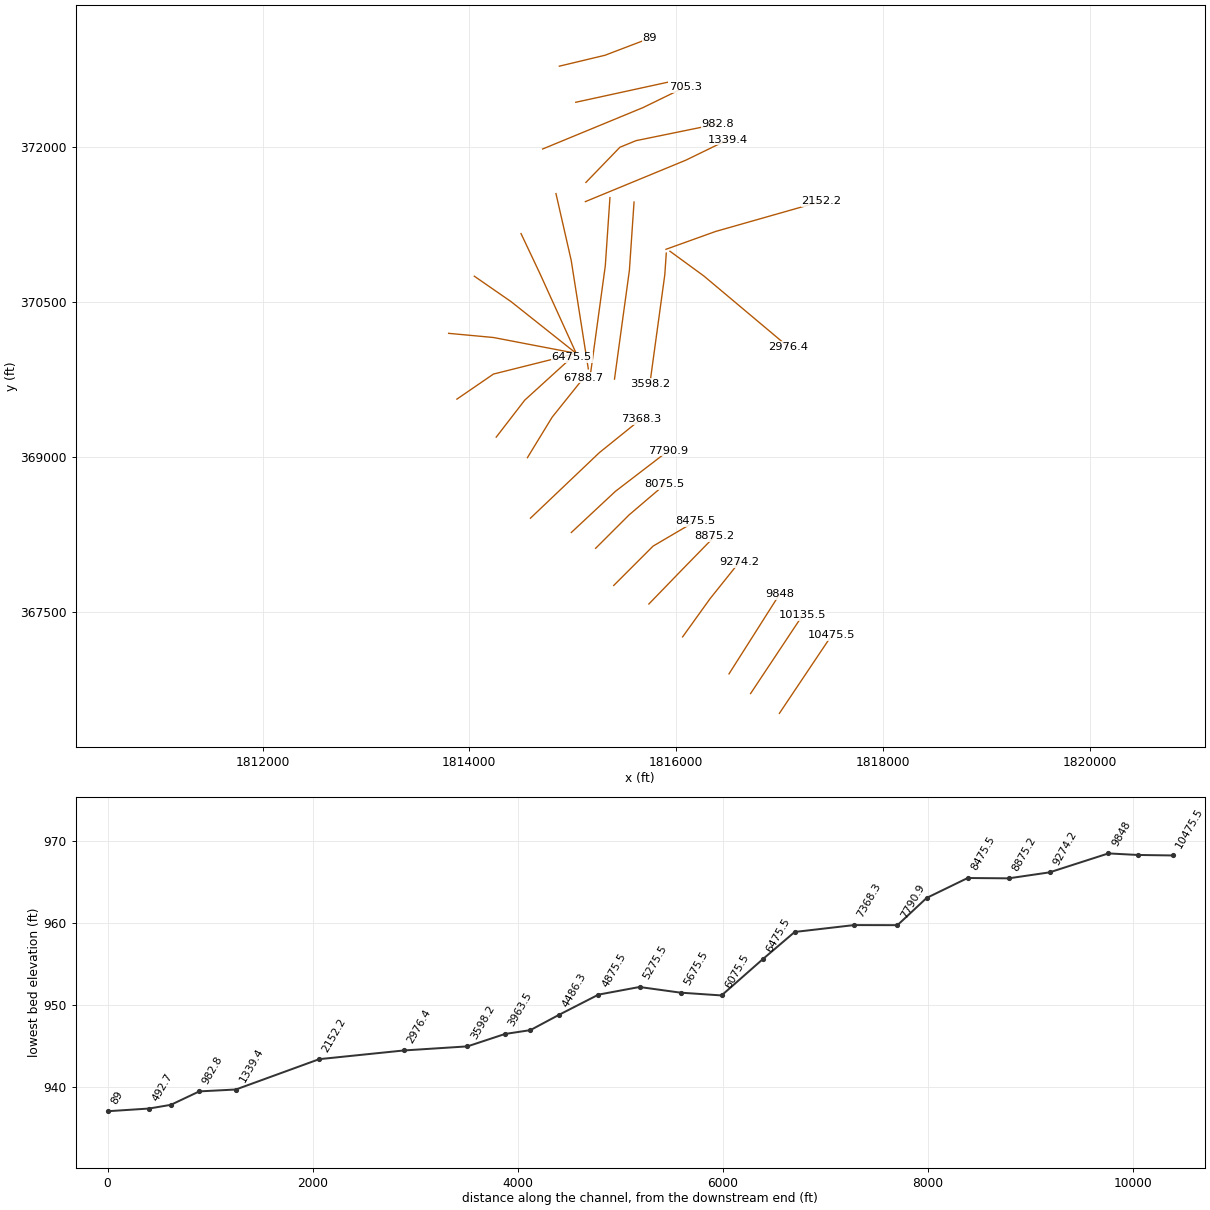
HEC-RAS study WhtdyCrk.prj: WhtdyCrk

--- WhtdyCrk.g01 (geometry) --- (continued)

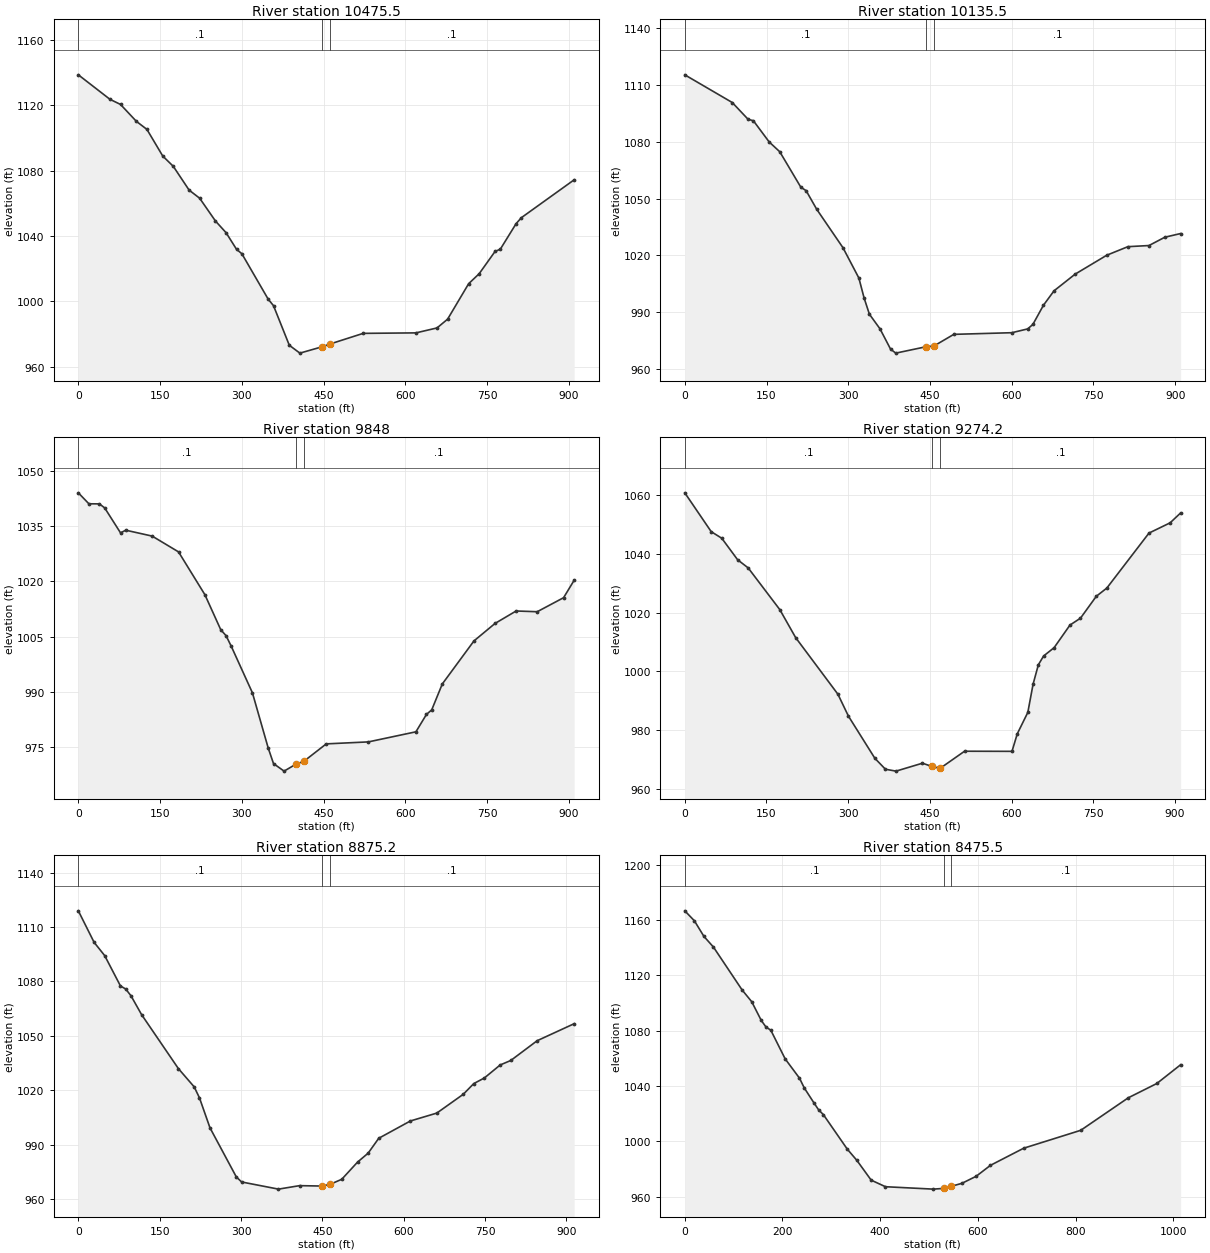
Type RM Length L Ch R = 1 ,10475.5 ,339.855,339.951,340.048
XS GIS Cut Line= 3
     1816998.051      366516.205     1817251.286      366894.222
      1817504.52       367272.24
#Sta/Elev= 30
       0 1138.78    58.1 1123.76    77.4 1120.64   106.5 1110.28   125.9 1105.33
   154.9 1089.02   174.3 1082.69   203.3 1068.13   222.7 1063.14   251.7 1049.17
   271.1 1042.05   290.4 1031.82   300.1 1029.14   348.5 1001.25   358.2   997.3
   387.2  973.04   406.6  968.21   447.5  972.11   462.5  973.87   522.8  980.32
   619.6  980.62   658.3  983.65   677.7  989.01   716.4 1010.78   735.7 1016.89
   764.8 1030.53   774.5 1031.92   803.5 1047.59   813.2 1051.24     910 1074.44
#Mann= 3 , 0 , 0
       0      .1       0   447.5    .045       0   462.5      .1       0
Bank Sta=447.5,462.5
XS Rating Curve= 0 ,0
Exp/Cntr=0.3,0.1

Type RM Length L Ch R = 1 ,10135.5 ,287.033,287.494,287.954
XS GIS Cut Line= 3
     1816719.581      366707.862     1816971.195      367086.961
     1817222.809      367466.059
#Sta/Elev= 30
       0 1115.48    87.1 1100.83   116.2 1091.95   125.9 1091.19   154.9 1079.96
   174.3 1074.79     213 1056.02   222.7  1054.2     242 1044.41   290.4 1023.98
   319.5 1007.98   329.1  997.41   338.8  988.86   358.2  981.15   377.6  970.42
   387.2  968.27   442.3  971.62   457.3  972.05   493.7   978.2   600.2  979.07
   629.3  981.08   638.9  983.48   658.3  993.63   677.7 1001.24   716.4 1010.05
   774.5 1020.07   813.2 1024.58   851.9 1025.18     881 1029.58     910 1031.53
#Mann= 3 , 0 , 0
       0      .1       0   442.3    .045       0   457.3      .1       0
Bank Sta=442.3,457.3
XS Rating Curve= 0 ,0
Exp/Cntr=0.3,0.1

Type RM Length L Ch R = 1 ,9848    ,574.725,573.816,571.774
XS GIS Cut Line= 3
     1816510.878      366898.244     1816754.678      367282.413
     1816998.478      367666.583
#Sta/Elev= 30
       0 1044.04    19.4 1041.06    38.7 1041.04    48.4 1039.94    77.4 1033.18
    87.1 1033.89   135.5 1032.29   183.9    1028   232.3 1016.37   261.4 1006.86
   271.1 1005.25   280.7 1002.36   319.5  989.73   348.5  974.73   358.2  970.51
   377.6  968.46   399.2  970.33   414.2  971.16     455  975.86   532.4   976.4
   619.6  979.14   638.9  983.86   648.6   985.1     668  992.13   726.1 1003.82
   764.8 1008.57   803.5 1011.95   842.2 1011.75   890.6 1015.56     910  1020.3
#Mann= 3 , 0 , 0
       0      .1       0   399.2    .045       0   414.2      .1       0
Bank Sta=399.2,414.2
XS Rating Curve= 0 ,0
Exp/Cntr=0.3,0.1

Type RM Length L Ch R = 1 ,9274.2  ,403.1,398.97,395.87
XS GIS Cut Line= 3
     1816062.226      367256.098     1816328.042      367626.297
     1816612.187      367981.497
#Sta/Elev= 30
       0 1060.67    48.5 1047.48    67.9 1045.25      97 1037.94   116.4 1035.17
   174.5    1021   203.6 1011.49   281.2  992.27   300.6   984.8   349.1   970.5
   368.5  966.79   387.9  966.15   436.4  968.84   453.7  967.76   468.7  967.07
   513.8  972.91   600.9  972.87   610.6  978.82     630  986.11   639.6  995.65
   649.3 1002.26     659 1005.26   678.3 1008.09   707.4 1015.76   726.7  1018.1
   755.8 1025.54   775.1 1028.33   852.5    1047   891.3 1050.48   910.6 1053.84
#Mann= 3 , 0 , 0
       0      .1       0   453.7    .045       0   468.7      .1       0
Bank Sta=453.7,468.7
XS Rating Curve= 0 ,0
Exp/Cntr=0.3,0.1

Type RM Length L Ch R = 1 ,8875.2  ,386.866,399.769,398.145
XS GIS Cut Line= 3
     1815736.201      367574.566     1816053.699      367902.628
     1816373.391      368230.356
#Sta/Elev= 30
       0 1118.95    29.1 1101.56    48.6 1094.25    77.7  1077.5    87.4 1075.81
    97.1 1072.08   116.6 1061.71   184.6 1031.88   213.7 1021.82   223.4 1015.77
   242.8  999.23   291.4  972.13   301.1  969.37   369.1  965.42     408  967.34
   448.7  967.12   463.7  967.99   485.8  970.85     515  980.35   534.5  985.27
     554  993.47   612.4 1003.02   661.1 1007.37   709.8 1017.72   729.3 1023.65
   748.8 1026.74     778 1033.92   797.5 1036.39   846.2  1047.3   914.4 1056.68
#Mann= 3 , 0 , 0
       0      .1       0   448.7    .045       0   463.7      .1       0
Bank Sta=448.7,463.7
XS Rating Curve= 0 ,0
Exp/Cntr=0.3,0.1

Type RM Length L Ch R = 1 ,8475.5  ,411.455,400,400.39
XS GIS Cut Line= 3
     1815396.411      367753.915      1815776.74      368134.642
      1816188.02      368376.287
#Sta/Elev= 30
       0 1166.68    19.6 1159.49    39.1 1148.23    58.7 1140.45   117.4 1109.44
     137 1100.98   156.6 1087.41   166.3 1082.64   176.1 1080.38   205.5 1059.64
   234.8 1045.71   244.6 1038.64   264.2 1027.93     274 1022.78   283.8  1019.3
   332.7  994.37   352.2   986.3   381.6  971.96   410.9   967.2   508.8  965.46
   530.6  965.99   545.6  967.49   567.4  969.66   596.6  974.75   625.8  982.66
   693.9  995.05   810.7 1007.99   908.1 1031.51   966.5 1041.84  1015.2  1055.4
#Mann= 3 , 0 , 0
       0      .1       0   530.6    .045       0   545.6      .1       0
Bank Sta=530.6,545.6
XS Rating Curve= 0 ,0
Exp/Cntr=0.3,0.1

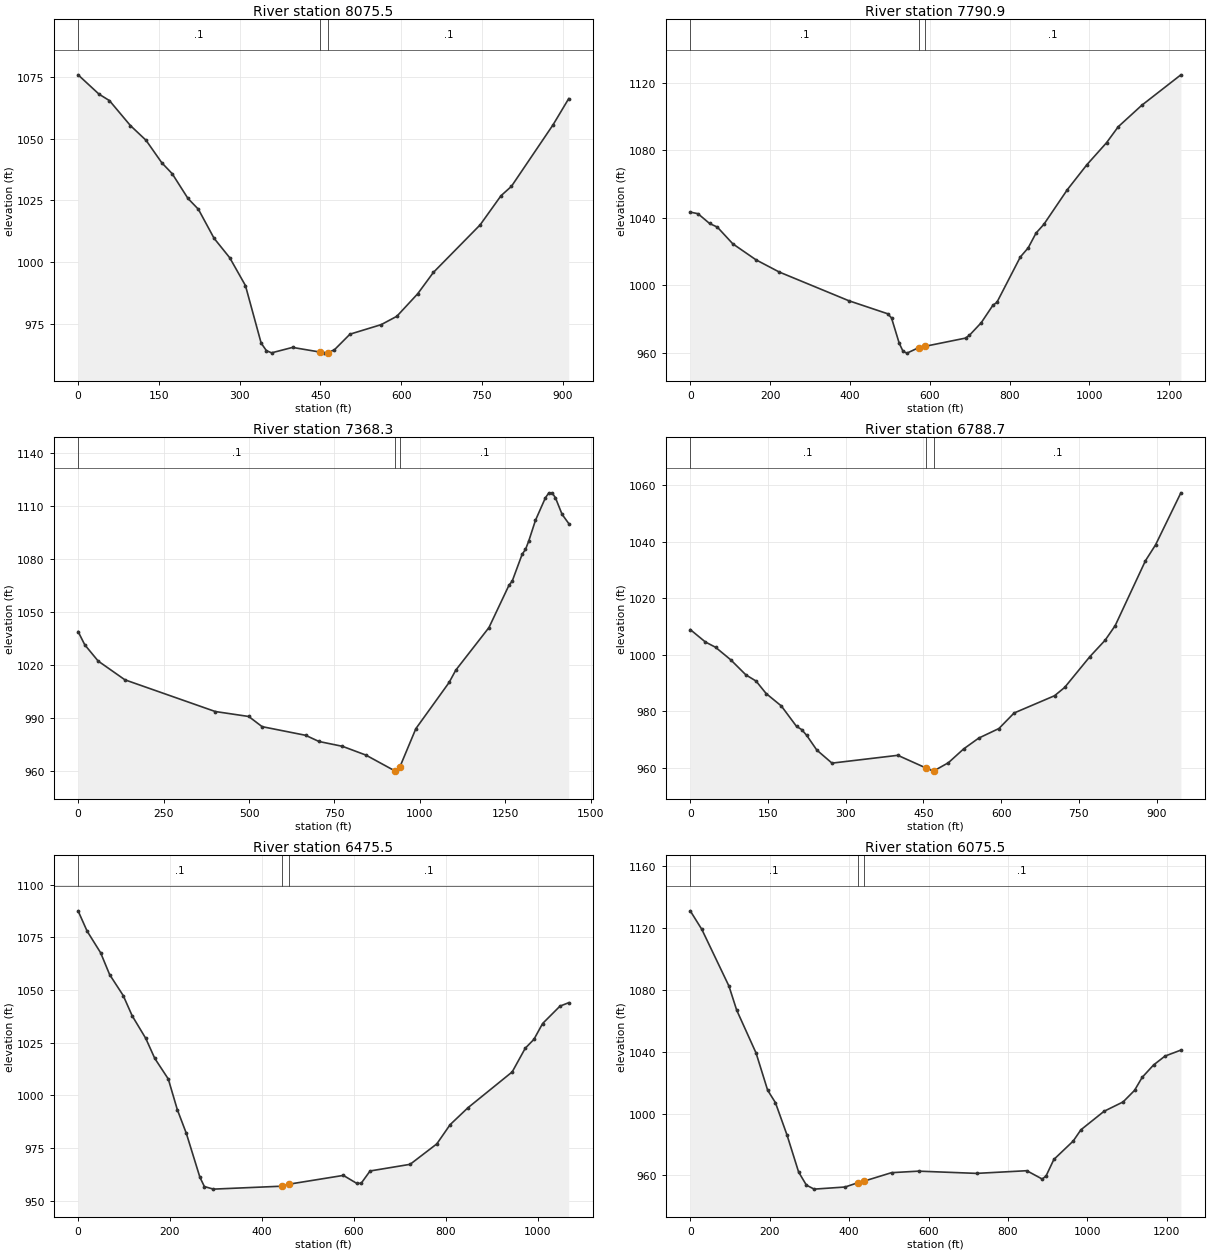
Type RM Length L Ch R = 1 ,8075.5  ,285.82,284.585,282.732
XS GIS Cut Line= 3
     1815221.345      368113.545     1815544.505      368436.266
     1815890.455      368731.342
#Sta/Elev= 30
       0 1075.93    38.9 1068.09    58.3 1065.47    97.2 1055.35   126.3 1049.36
   155.5 1040.26   174.9 1035.81   204.1 1025.79   223.5 1021.39   252.6 1009.63
   281.8  1001.7   310.9  990.44   340.1  967.09   349.8  964.04   359.5  963.15
   398.4  965.35   449.2  963.47   456.7  963.03   464.2  963.27   476.1  964.37
   505.1  970.72   563.1  974.59   592.1  977.97   630.8  987.09   659.9  995.74
   746.9 1015.07   785.6 1026.88     805 1030.69   882.4 1055.69   911.4 1066.28
#Mann= 3 , 0 , 0
       0      .1       0   449.2    .045       0   464.2      .1       0
Bank Sta=449.2,464.2
XS Rating Curve= 0 ,0
Exp/Cntr=0.3,0.1

Type RM Length L Ch R = 1 ,7790.9  ,423.834,422.621,423.103
XS GIS Cut Line= 3
     1814986.521      368266.771     1815411.582      368663.835
     1815925.163      369057.708
#Sta/Elev= 30
       0 1043.39    19.4 1042.44    48.5 1036.63    67.9 1034.49   106.6 1024.57
   164.8 1015.06     223 1007.83   397.5  990.77   494.4  983.08   504.1  980.61
   523.5  965.52   533.2   960.7   542.9  959.71   572.4  962.99   587.4  963.72
   689.5  968.63   699.3   970.3   728.8  977.75   758.2  988.16     768   989.8
   826.8 1016.78   846.4 1022.15   866.1 1030.94   885.7 1036.13   944.5  1056.7
   993.5 1071.52  1042.6 1084.54    1072 1094.05  1130.8 1106.76  1228.9 1124.85
#Mann= 3 , 0 , 0
       0      .1       0   572.4    .045       0   587.4      .1       0
Bank Sta=572.4,587.4
XS Rating Curve= 0 ,0
Exp/Cntr=0.3,0.1

Type RM Length L Ch R = 1 ,7368.3  ,572.841,579.534,584.37
XS GIS Cut Line= 3
     1814591.053      368404.947     1815257.513      369039.186
     1815658.341      369362.647
#Sta/Elev= 30
       0 1038.82    19.6 1031.29    58.7  1022.1     137 1011.46   401.3  993.49
   499.2  990.68   538.3  984.92   665.5  980.02   704.7  976.51   773.2  973.78
   841.7  968.83   926.6  959.86   929.7  959.72   941.6  962.26     988  983.78
  1085.2 1009.94  1104.7 1016.91  1201.8 1041.06  1260.2 1064.97  1269.9 1067.41
    1299 1082.65  1308.7 1085.32  1318.5 1090.28  1337.9 1101.85  1367.1 1114.66
  1376.8 1117.28  1386.5  1117.4  1396.2 1114.64  1415.6 1105.25  1435.1 1100.02
#Mann= 3 , 0 , 0
       0      .1       0   926.6    .045       0   941.6      .1       0
Bank Sta=926.6,941.6
XS Rating Curve= 0 ,0
Exp/Cntr=0.3,0.1

Type RM Length L Ch R = 1 ,6788.7  ,315.285,313.26,309.79
XS GIS Cut Line= 3
     1814561.633      368990.427     1814800.847       369382.28
     1815105.638       369762.88
#Sta/Elev= 30
       0 1008.93    29.3 1004.52    48.8 1002.67    78.1  998.24   107.4   992.9
     127  990.72   146.5   986.3   175.8  981.91   205.1  974.69   214.9  973.58
   224.7  971.52   244.2  966.33   273.5  961.71   400.5  964.47   454.9  959.99
   468.9  958.88   469.9  958.95   498.1  961.85   527.4  966.71   556.6  970.55
   595.6  973.94   624.9  979.43   702.9  985.53   722.4  988.46   771.2  999.38
   800.4 1005.13   819.9  1010.3   878.4 1033.28   897.9 1038.89   946.7 1057.26
#Mann= 3 , 0 , 0
       0      .1       0   454.9    .045       0   469.9      .1       0
Bank Sta=454.9,469.9
XS Rating Curve= 0 ,0
Exp/Cntr=0.3,0.1

Type RM Length L Ch R = 1 ,6475.5  ,407.078,400,388.547
XS GIS Cut Line= 4
     1814259.935      369189.168     1814535.639      369546.839
     1814886.408      369866.051     1814991.369      369961.569
#Sta/Elev= 30
       0 1087.53    19.6 1077.93    49.1 1067.63    68.7 1057.28    98.2 1047.37
   117.8 1037.72   147.3 1027.04   166.9 1017.56   196.3 1007.79     216  993.23
   235.6  981.99   265.1   961.2   274.9  956.76   294.5  955.54   444.1  956.94
   459.1  957.89   577.4  962.05   606.5  958.27   616.1  958.31   635.5  964.15
   722.6   967.3   780.7  976.99   809.7  986.11   848.4  994.12   944.8 1011.13
   973.2 1022.36   992.1 1026.58    1011 1034.09  1048.9 1042.35  1067.8 1043.95
#Mann= 3 , 0 , 0
       0      .1       0   444.1    .045       0   459.1      .1       0
Bank Sta=444.1,459.1
XS Rating Curve= 0 ,0
Exp/Cntr=0.3,0.1

Type RM Length L Ch R = 1 ,6075.5  ,417.075,400,387.666
XS GIS Cut Line= 5
     1813879.706      369556.701     1814233.271      369799.344
     1814818.582      369945.872     1814976.709      369985.458
     1815015.498      369995.169
#Sta/Elev= 30
       0 1131.11    29.2 1119.09    97.5 1082.41   116.9  1066.9   165.7 1039.16
   194.9 1015.08   214.4 1007.09   243.6  986.16   272.9  962.15   292.4  953.74
   311.9  951.14   389.8  952.51   421.3  955.22   436.3  956.21   506.7  961.78
   574.8  962.77   720.8  961.32   847.3  963.05   886.2  957.65   895.9  959.73
   915.4  970.33   964.1  982.23   983.5  989.51  1041.8 1001.48  1089.7 1007.53
  1118.5 1014.99  1137.7 1023.41  1166.4 1031.42  1195.2 1037.18  1235.2 1041.04
#Mann= 3 , 0 , 0
       0      .1       0   421.3    .045       0   436.3      .1       0
Bank Sta=421.3,436.3
XS Rating Curve= 0 ,0
Exp/Cntr=0.3,0.1

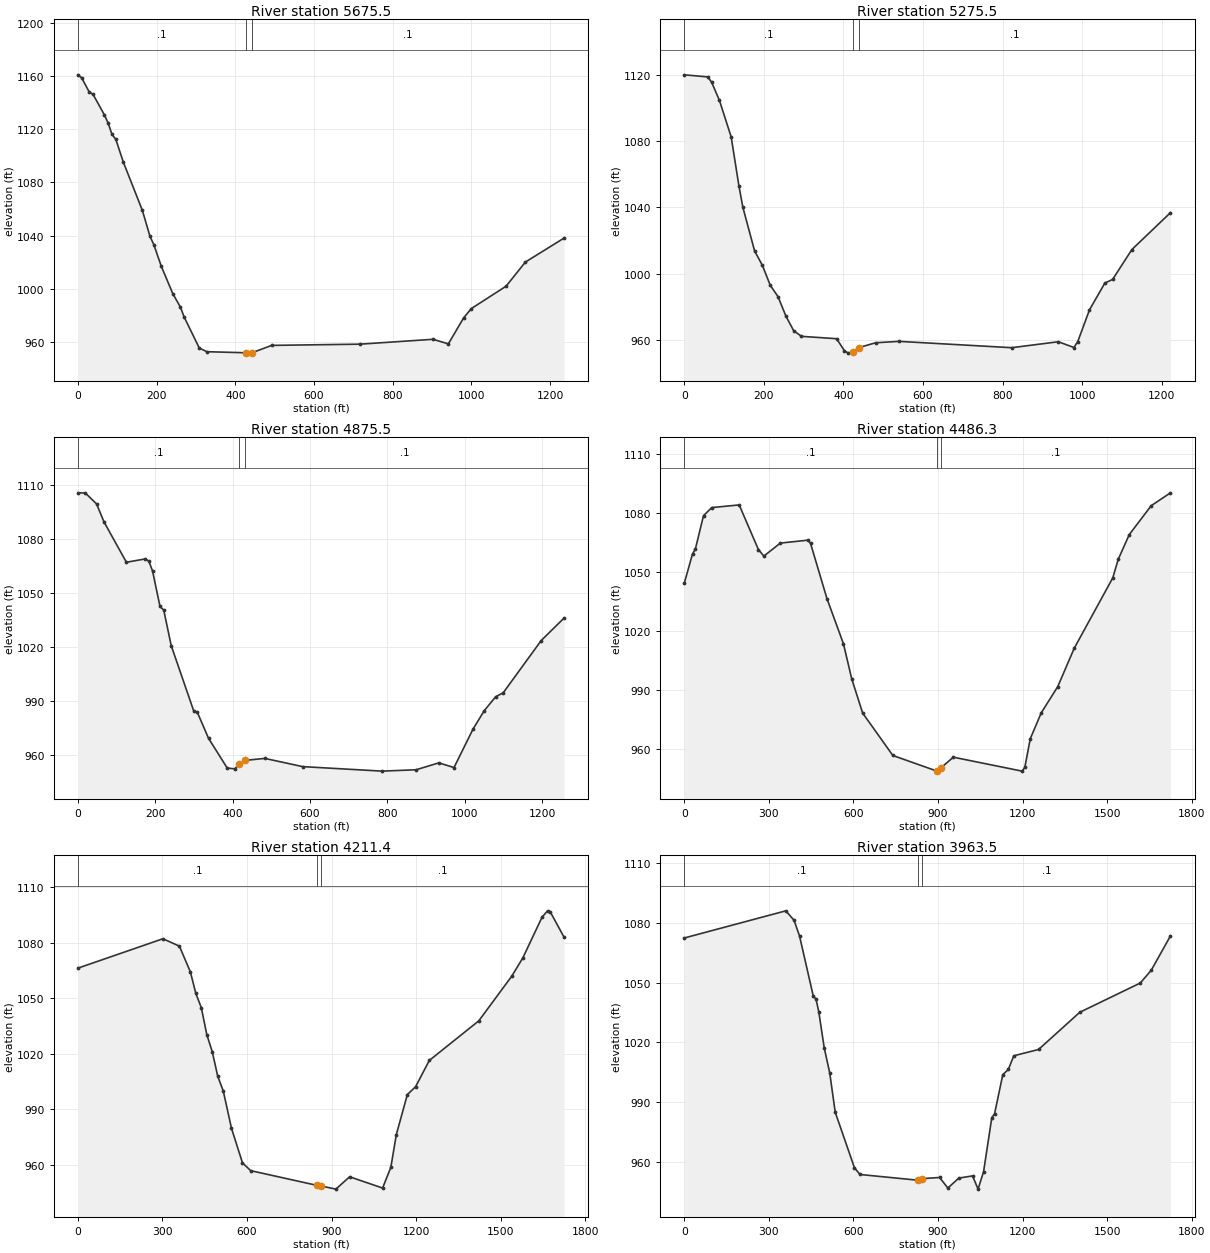
Type RM Length L Ch R = 1 ,5675.5  ,411.627,400,389.822
XS GIS Cut Line= 4
     1813799.742       370193.25     1814231.831      370153.168
     1814816.527      370041.104     1815018.736      370002.348
#Sta/Elev= 30
       0 1160.96     9.6 1158.74    28.9 1148.03    38.6 1146.26    67.5 1130.78
    77.1 1124.52    86.8 1116.05    96.4 1112.44   115.7 1095.14   163.9 1058.93
   183.2 1039.44   192.9 1033.21   212.2 1016.72   241.1  996.35   260.4  986.21
     270  978.74   308.6  955.28   327.9  952.55   426.4  951.75   433.9  951.48
   441.4  951.65   492.5   957.3     717  958.23   902.4  961.89   941.4  958.45
   980.5  978.17    1000  985.06  1088.1 1001.87  1137.1 1020.03  1235.2 1038.05
#Mann= 3 , 0 , 0
       0      .1       0   426.4    .045       0   441.4      .1       0
Bank Sta=426.4,441.4
XS Rating Curve= 0 ,0
Exp/Cntr=0.3,0.1

Type RM Length L Ch R = 1 ,5275.5  ,411.957,400,389.199
XS GIS Cut Line= 4
     1814048.163      370746.021     1814403.184      370500.237
      1814862.32      370135.346     1815021.621      370008.745
#Sta/Elev= 30
       0 1119.84    58.9 1118.58    68.7 1115.35    88.3 1104.42   117.8 1082.42
   137.4 1052.66   147.2 1039.98   176.6 1013.77   196.3    1005   215.9  993.08
   235.5  986.21   255.2  974.55   274.8   965.7   294.4  962.28   382.7  960.86
   402.4  953.61   412.2  952.17   424.3  953.02   439.3  955.55   480.7  958.41
   539.3  959.26   822.8  955.44   940.1  959.03   979.2  955.55   988.9  959.17
  1018.3  978.24    1057  994.42  1076.4  996.56  1124.9  1014.6  1221.8  1036.8
#Mann= 3 , 0 , 0
       0      .1       0   424.3    .045       0   439.3      .1       0
Bank Sta=424.3,439.3
XS Rating Curve= 0 ,0
Exp/Cntr=0.3,0.1

Type RM Length L Ch R = 1 ,4875.5  ,384.952,389.132,384.089
XS GIS Cut Line= 4
     1814499.664      371158.652     1814681.067      370774.501
     1814940.002      370204.591     1815025.288      370016.878
#Sta/Elev= 30
       0 1105.85    19.3 1105.75    48.3 1099.72    67.6 1089.72   125.5 1067.28
   173.8 1069.11   183.4 1067.99   193.1 1062.45   212.4 1042.75   222.1 1040.68
   241.4 1020.97   299.3  984.86     309  983.89   337.9  969.48   386.2  952.95
   405.5  952.51   417.3  955.05   432.3   957.2   483.5  958.31   581.3  953.74
   786.7  951.24   874.7     952   933.4  955.83   972.6  953.23  1021.5  974.47
  1050.8  984.83  1080.3  992.56  1099.9  994.78  1198.1  1023.8    1257 1036.26
#Mann= 3 , 0 , 0
       0      .1       0   417.3    .045       0   432.3      .1       0
Bank Sta=417.3,432.3
XS Rating Curve= 0 ,0
Exp/Cntr=0.3,0.1

Type RM Length L Ch R = 1 ,4486.3  ,292.474,274.954,265.581
XS GIS Cut Line= 3
     1814837.713      371545.107     1814984.895      370899.748
     1815150.256      369849.777
#Sta/Elev= 30
       0 1044.36    29.2 1059.27    38.9 1061.52    68.1 1078.67    97.3 1082.78
   194.7 1084.14   262.8 1061.45   282.3 1058.12   340.7 1064.73     438 1066.21
   447.8 1064.59   506.2 1036.44   564.6 1013.51   593.8  995.75   632.7  978.29
   739.9   956.7   895.8  948.79   910.8  950.45   954.5  955.84  1198.3  948.75
    1208  950.61  1227.5  965.25  1266.5  978.44    1325  991.75  1383.5 1011.29
  1520.1 1047.03  1539.6 1056.51  1578.6 1069.05  1656.6 1083.76  1724.8 1090.29
#Mann= 3 , 0 , 0
       0      .1       0   895.8    .045       0   910.8      .1       0
Bank Sta=895.8,910.8
XS Rating Curve= 0 ,0
Exp/Cntr=0.3,0.1

Type RM Length L Ch R = 1 ,4211.4  ,247.929,247.841,249.161
XS GIS Cut Line= 3
     1815359.661      371506.626     1815314.663      370846.227
     1815170.499      369793.137
#Sta/Elev= 30
       0 1066.23   301.8 1082.12   360.2 1078.13   399.1  1064.3   418.6 1052.58
     438  1044.9   457.5 1030.35     477 1021.04   496.4  1007.8   515.9  999.93
   545.1  979.75   584.1  961.09   613.3  956.88   847.9  948.96   862.9  948.61
   915.5  946.91   964.2  953.58  1081.2  947.49  1110.5   958.7    1130   976.4
    1169  997.96  1198.3 1002.24    1247 1016.42  1422.5 1037.79  1539.6 1061.94
  1578.6 1071.73  1646.8 1093.75  1666.3  1097.2  1676.1 1096.61  1724.8 1083.02
#Mann= 3 , 0 , 0
       0      .1       0   847.9    .045       0   862.9      .1       0
Bank Sta=847.9,862.9
XS Rating Curve= 0 ,0
Exp/Cntr=0.3,0.1

Type RM Length L Ch R = 1 ,3963.5  ,366.988,365.326,362.449
XS GIS Cut Line= 3
     1815592.708      371463.821      1815547.71      370803.423
     1815403.546      369750.332
#Sta/Elev= 30
       0 1072.32   360.2 1085.93   389.4 1081.17   408.8 1073.33   457.5 1043.22
   467.2 1041.66     477  1035.4   496.4 1017.23   515.9 1004.71   535.4  984.98
   603.5   957.2     623  953.78     830  950.89     845  951.72   905.7  952.27
     935  946.99     974  951.98  1022.7  953.07  1042.2  946.44  1061.7  955.16
    1091  982.31  1100.7   984.2    1130 1003.87  1149.5 1006.41    1169 1013.29
  1256.8 1016.43    1403 1035.08  1617.6 1049.74  1656.6 1056.13  1724.8 1073.37
#Mann= 3 , 0 , 0
       0      .1       0     830    .045       0     845      .1       0
Bank Sta=830,845
XS Rating Curve= 0 ,0
Exp/Cntr=0.3,0.1

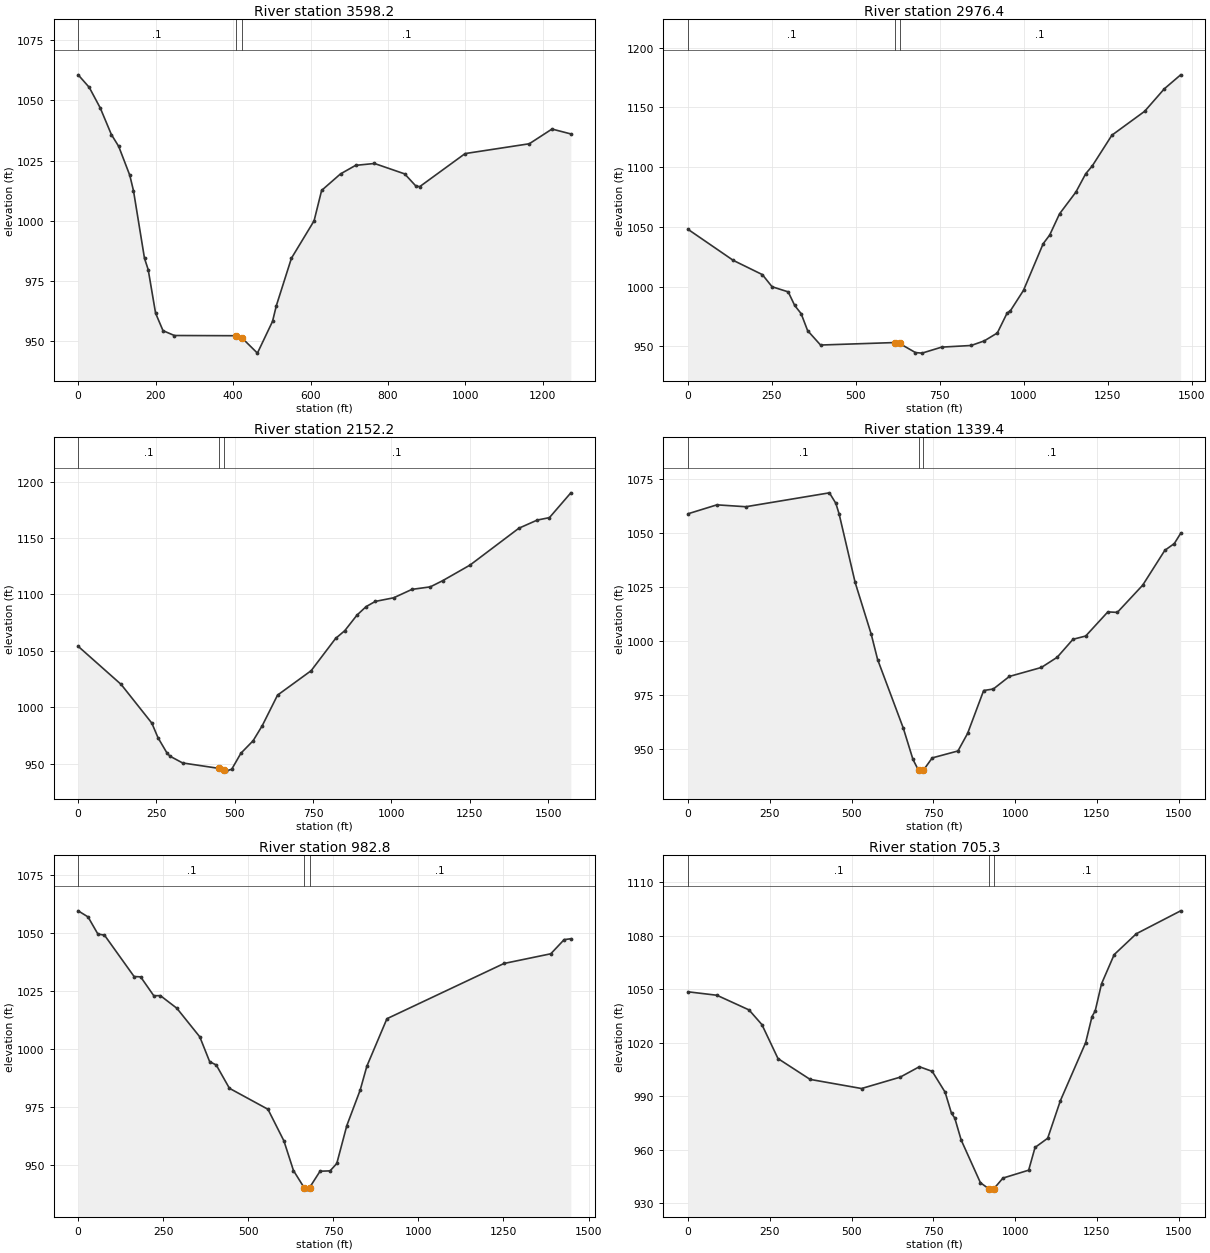
Type RM Length L Ch R = 1 ,3598.2  ,594.341,621.849,648.95
XS GIS Cut Line= 3
     1815904.381      370969.532     1815890.146      370760.618
     1815745.982      369707.528
#Sta/Elev= 30
       0 1060.67    28.6 1055.45    57.1 1046.86    85.7 1035.85   104.7  1030.9
   133.3 1018.88   142.8 1012.51   171.3  984.33   180.8  979.68   199.9  961.55
   219.1  954.27   248.4  952.26     408  952.17     423  951.25   462.9  944.93
   501.9  958.13   511.7  964.63   550.7  984.39   609.2  999.95   628.7  1012.6
   677.5 1019.47   716.5 1023.02   765.2  1023.8   843.2 1019.47   872.5 1014.35
   882.3  1014.2   999.3 1027.92    1165    1032  1223.6 1038.12  1272.3 1036.09
#Mann= 3 , 0 , 0
       0      .1       0     408    .045       0     423      .1       0
Bank Sta=408,423
XS Rating Curve= 0 ,0
Exp/Cntr=0.3,0.1

Type RM Length L Ch R = 1 ,2976.4  ,800.13,824.18,846.181
XS GIS Cut Line= 3
      1815940.22      370987.451     1816266.889      370748.983
      1817080.81      370065.378
#Sta/Elev= 30
       0 1047.96   134.8    1022   221.5 1010.08   250.4  999.95   298.5  995.64
   317.8  984.29     337  977.44   356.3  963.24   394.8   951.2   615.2  953.27
   630.2  952.51   677.5   944.9     697  944.43   755.5  949.45   843.3  950.82
   882.3  954.65   921.3  961.27   950.5  977.96   960.3  979.87   999.3  996.95
  1057.8  1035.9  1077.3 1043.19  1106.6  1060.9  1155.3 1079.09  1184.6 1094.45
  1204.1 1100.97  1262.6 1126.67  1360.1 1146.65  1418.6 1165.42  1467.4 1177.15
#Mann= 3 , 0 , 0
       0      .1       0   615.2    .045       0   630.2      .1       0
Bank Sta=615.2,630.2
XS Rating Curve= 0 ,0
Exp/Cntr=0.3,0.1

Type RM Length L Ch R = 1 ,2152.2  ,811.346,812.786,814.282
XS GIS Cut Line= 3
     1815901.502      371006.464     1816381.106      371178.949
     1817403.436       371469.85
#Sta/Elev= 30
       0    1054   137.2  1020.2   235.2  985.89   254.8  972.99   284.2  959.08
     294  956.47   333.3  950.63   449.1  945.81   464.1  944.14   470.5  943.37
   490.1  945.03   519.4  959.21   558.4   970.3   587.7  983.73   636.4 1010.74
   743.7  1032.4   821.7 1060.98     851 1067.86     890 1081.67   919.2  1089.2
   948.5  1093.8    1007    1097  1065.5 1104.47    1124 1106.69    1163  1112.1
  1250.8    1126  1406.8 1158.68  1465.3 1165.88  1504.3 1168.07  1572.6 1190.04
#Mann= 3 , 0 , 0
       0      .1       0   449.1    .045       0   464.1      .1       0
Bank Sta=449.1,464.1
XS Rating Curve= 0 ,0
Exp/Cntr=0.3,0.1

Type RM Length L Ch R = 1 ,1339.4  ,360.595,356.6,352.549
XS GIS Cut Line= 3
     1815122.398      371467.923     1816094.347      371869.072
     1816503.367      372068.389
#Sta/Elev= 30
       0 1058.93    88.4 1063.07   176.9  1062.2   432.4 1068.64     452  1063.8
   461.9 1058.97     511 1027.16   560.1 1003.22   579.8   991.4   658.4  959.57
   687.9  945.09   704.9  940.06   707.5  939.67   719.9  940.12   746.8   945.8
   825.5  949.01   854.9  957.13   904.1  977.03   933.6  977.72   982.7  983.55
  1080.5  987.71  1128.9  992.43  1177.3 1000.77  1216.1 1002.28  1283.8 1013.46
  1312.9 1013.24  1390.3 1025.83  1458.1    1042  1487.1 1045.13  1506.5 1049.87
#Mann= 3 , 0 , 0
       0      .1       0   704.9    .045       0   719.9      .1       0
Bank Sta=704.9,719.9
XS Rating Curve= 0 ,0
Exp/Cntr=0.3,0.1

Type RM Length L Ch R = 1 ,982.8   ,273.222,277.494,281.766
XS GIS Cut Line= 4
     1815127.154       371653.41     1815456.094      371993.954
     1815612.272      372057.675     1816401.778      372219.381
#Sta/Elev= 30
       0 1059.68      29 1057.05      58 1049.63    77.3 1049.18   164.3  1031.3
   183.6 1031.15   222.2    1023   241.6 1023.04   289.9 1017.61   357.5 1005.22
   386.5   994.5   405.8  993.08   444.5  983.01   557.8  973.94   604.7  960.28
   632.8  947.46   665.1  939.84   671.6  939.44   680.1  940.09   710.9  947.18
   740.4  947.33   760.1  950.53   789.6  966.91   828.9  982.26   848.5  992.57
   907.5 1013.07  1251.5 1036.93  1389.1 1041.12  1428.4 1047.25    1448 1047.61
#Mann= 3 , 0 , 0
       0      .1       0   665.1    .045       0   680.1      .1       0
Bank Sta=665.1,680.1
XS Rating Curve= 0 ,0
Exp/Cntr=0.3,0.1

Type RM Length L Ch R = 1 ,705.3   ,216.643,212.638,208.633
XS GIS Cut Line= 3
     1814708.621      371976.822      1815680.57      372377.971
      1816089.59      372577.288
#Sta/Elev= 30
       0 1048.52    88.4 1046.58   186.7 1038.34     226 1030.11   275.2 1011.05
   373.4  999.37   530.7  994.25   648.6 1000.61   707.5 1006.48   746.8 1003.88
   786.2  992.19   805.8  980.27   815.6  977.76   835.3  965.37   894.2  941.39
   919.4  938.05   933.6   937.8   934.4  937.83     963  943.99  1041.7  948.43
  1061.2  961.18  1099.9  966.35  1138.6  987.39  1216.1 1020.07  1235.4 1034.63
  1245.1 1037.77  1264.5    1053  1303.2 1069.38  1370.9 1081.09  1506.5 1093.95
#Mann= 3 , 0 , 0
       0      .1       0   919.4    .045       0   934.4      .1       0
Bank Sta=919.4,934.4
XS Rating Curve= 0 ,0
Exp/Cntr=0.3,0.1

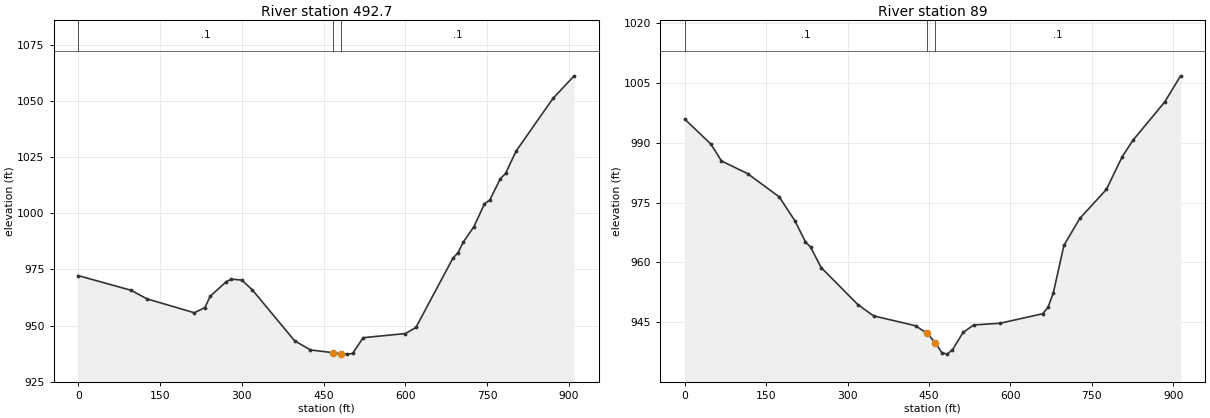
Type RM Length L Ch R = 1 ,492.7   ,403.381,403.713,406.976
XS GIS Cut Line= 3
     1815028.871      372428.914     1815473.414      372525.905
     1815917.956      372622.896
#Sta/Elev= 30
       0  972.26    96.8  965.75   125.9  961.94     213  955.74   232.3  958.07
     242  963.08   271.1  969.49   280.7  970.71   300.1  970.28   319.5  965.89
   396.9   943.3     426  939.21   466.5  938.02   481.5  937.52   493.7  937.35
   503.4  937.66   522.8  944.66   600.2   946.5   619.6  949.21   687.3  979.96
     697  982.52   706.7  987.28   726.1  994.06   745.4 1004.22   755.1 1005.88
   774.5 1015.36   784.1 1017.71   803.5 1027.69   871.3 1051.14     910 1061.14
#Mann= 3 , 0 , 0
       0      .1       0   466.5    .045       0   481.5      .1       0
Bank Sta=466.5,481.5
XS Rating Curve= 0 ,0
Exp/Cntr=0.3,0.1

Type RM Length L Ch R = 1 ,89      ,88.955,88.955,86.025
XS GIS Cut Line= 3
     1814870.288      372778.264     1815312.011      372883.894
     1815741.522      373047.639
#Sta/Elev= 30
       0  995.93    48.3  989.65    67.6  985.45     116  982.26   173.9  976.46
   202.9  970.46   222.3  965.17   231.9  963.84   251.2  958.74   318.9  949.45
   347.9  946.61   425.2  944.14   446.7  942.22   461.7  939.86   473.7  937.38
   483.5  937.02   493.3   938.1   512.9  942.46   532.4  944.33   581.3  944.77
   659.6  947.15   669.3  948.73   679.1  952.34   698.7  964.28     728  971.05
   776.9   978.3   806.3  986.56   825.8  990.62   884.5 1000.25   913.8  1006.8
#Mann= 3 , 0 , 0
       0      .1       0   446.7    .045       0   461.7      .1       0
Bank Sta=446.7,461.7
XS Rating Curve= 0 ,0
Exp/Cntr=0.3,0.1

Chan Stop Cuts=-1
Use User Specified Reach Order=0